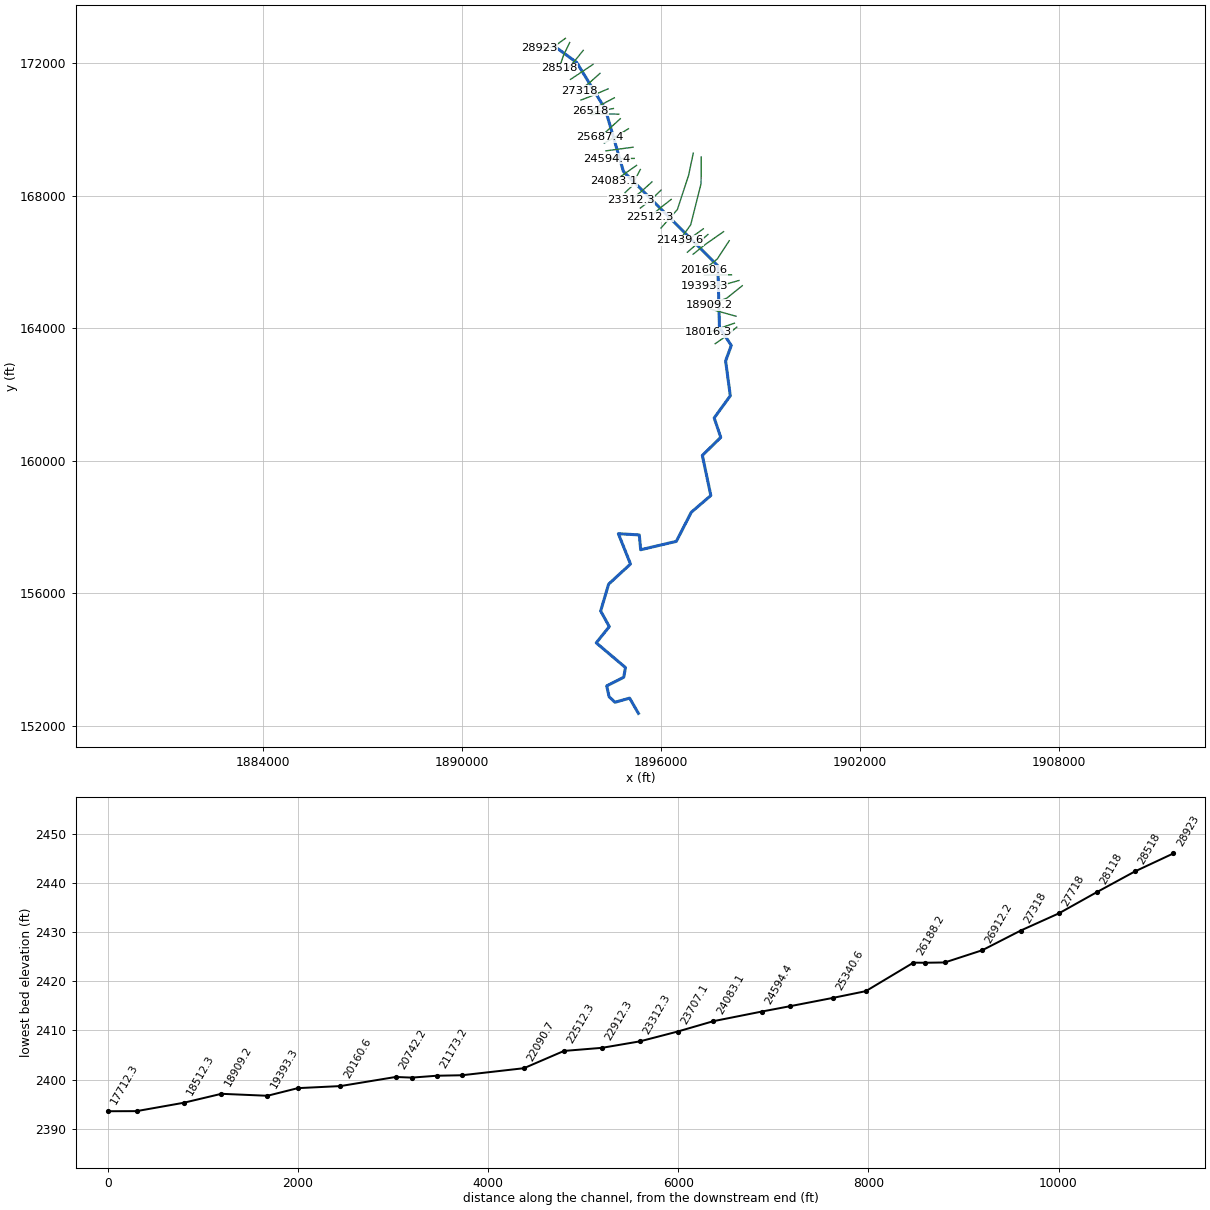
--- RghthndFrk.prj (project) ---

Proj Title=RghthndFrk
Current Plan=p01
Default Exp/Contr=0,0
English Units
Geom File=g01
Flow File=f01
Plan File=p01
BEGIN DESCRIPTION:
END DESCRIPTION:
DSS Export Rating Curves= 0
DSS Export Rating Curve Sorted= 0
DSS Export Volume Flow Curves= 0
DXF OffsetX= 0
DXF OffsetY= 0
DXF ScaleX= 0
DXF ScaleY= 0

--- RghthndFrk.p01 (plan) ---

Plan Title=Floodplain
Program Version=4.00
Geom File=g01
Flow File=f01
K Sum by GR=0
Std Step Tol=0.01
Critical Tol=0.01
Num of Std Step Trials=20
Max Error Tol=0.3
Flow Tol Ratio=0.001
Split Flow NTrial=30
Split Flow Tol=0.02
Split Flow Ratio=0.02
Log Output Level=0
Friction Slope Method=1
Unsteady Friction Slope Method=2
Unsteady Bridges Friction Slope Method=1
Global Log Level=0
CheckData=False
Run HTab=0
Run UNet=0
Run PostProcess=0
UNET Theta=0
UNET Theta Warmup=0
UNET ZTol=0
UNET ZSATol=0
UNET MxIter=0
UNET MaxInSteps=0
UNET DtIC=0
UNET DtMin=0
UNET MaxCRTS=0
UNET WFStab=0
UNET SFStab=0
UNET WFX=0
UNET SFX=0
UNET DSS MLevel=0
UNET DZMax Abort=0
UNET Convert EG Bridges=0
UNET Use Existing IB Tables=0
UNET Froude Limit=0
UNET Froude Power=0
Write IC File=0
Echo Input=False
Echo Output=False
Write Detailed=0

--- RghthndFrk.f01 (steady flow) ---

Flow Title=NFF Regression Equation
Program Version=4.10
Number of Profiles= 1
Profile Names=P100yr
River Rch & RM=RghthndFrk,Main            ,28923
492.1333
River Rch & RM=RghthndFrk,Main            ,28518
626.0708
River Rch & RM=RghthndFrk,Main            ,28118
661.3199
River Rch & RM=RghthndFrk,Main            ,24889.2
722.8619
River Rch & RM=RghthndFrk,Main            ,21439.6
799.8558
River Rch & RM=RghthndFrk,Main            ,21173.2
1156.502
River Rch & RM=RghthndFrk,Main            ,19712.3
1261.887
River Rch & RM=RghthndFrk,Main            ,14912.3
1382.934
River Rch & RM=RghthndFrk,Main            ,7664.8
1532.993
River Rch & RM=RghthndFrk,Main            ,7192.7
1891.912
River Rch & RM=RghthndFrk,Main            ,1341.6
2013.587
River Rch & RM=RghthndFrk,Main            ,822.5
    2502
Boundary for River Rch & Prof#=RghthndFrk,Main            , 1
Up Type= 0
Dn Type= 1
Dn Known WS=2370.1
DSS Import GetInterval= 0
DSS Import GetPeak= 0
DSS Import FillOption= 0

--- RghthndFrk.g01 (geometry) ---

Geom Title=USGS 3m DEM
Program Version=4.10

River Reach=RghthndFrk      ,Main
Reach XY= 30
     1892775.604       172509.63     1893450.083      172017.442
     1894314.667      170604.682     1894859.425      168727.207
     1897707.896      165880.723     1897756.073      164025.255
     1898112.844      163477.078     1897942.271      163010.932
     1898082.896      161957.546     1897597.219      161289.578
     1897795.136      160702.338     1897240.448      160158.067
     1897495.656      158948.432     1896905.813      158441.921
     1896455.292      157564.317     1895379.852      157311.489
     1895338.104      157758.327     1894706.594      157796.088
     1895072.513      156880.234     1894413.625      156273.953
      1894172.74      155462.755     1894433.157        154991.4
     1894039.927      154501.817     1894921.731      153755.515
     1894868.735      153463.553     1894355.031      153202.338
     1894426.594      152876.767     1894604.091      152708.663
     1895046.471      152832.394     1895312.426      152372.753

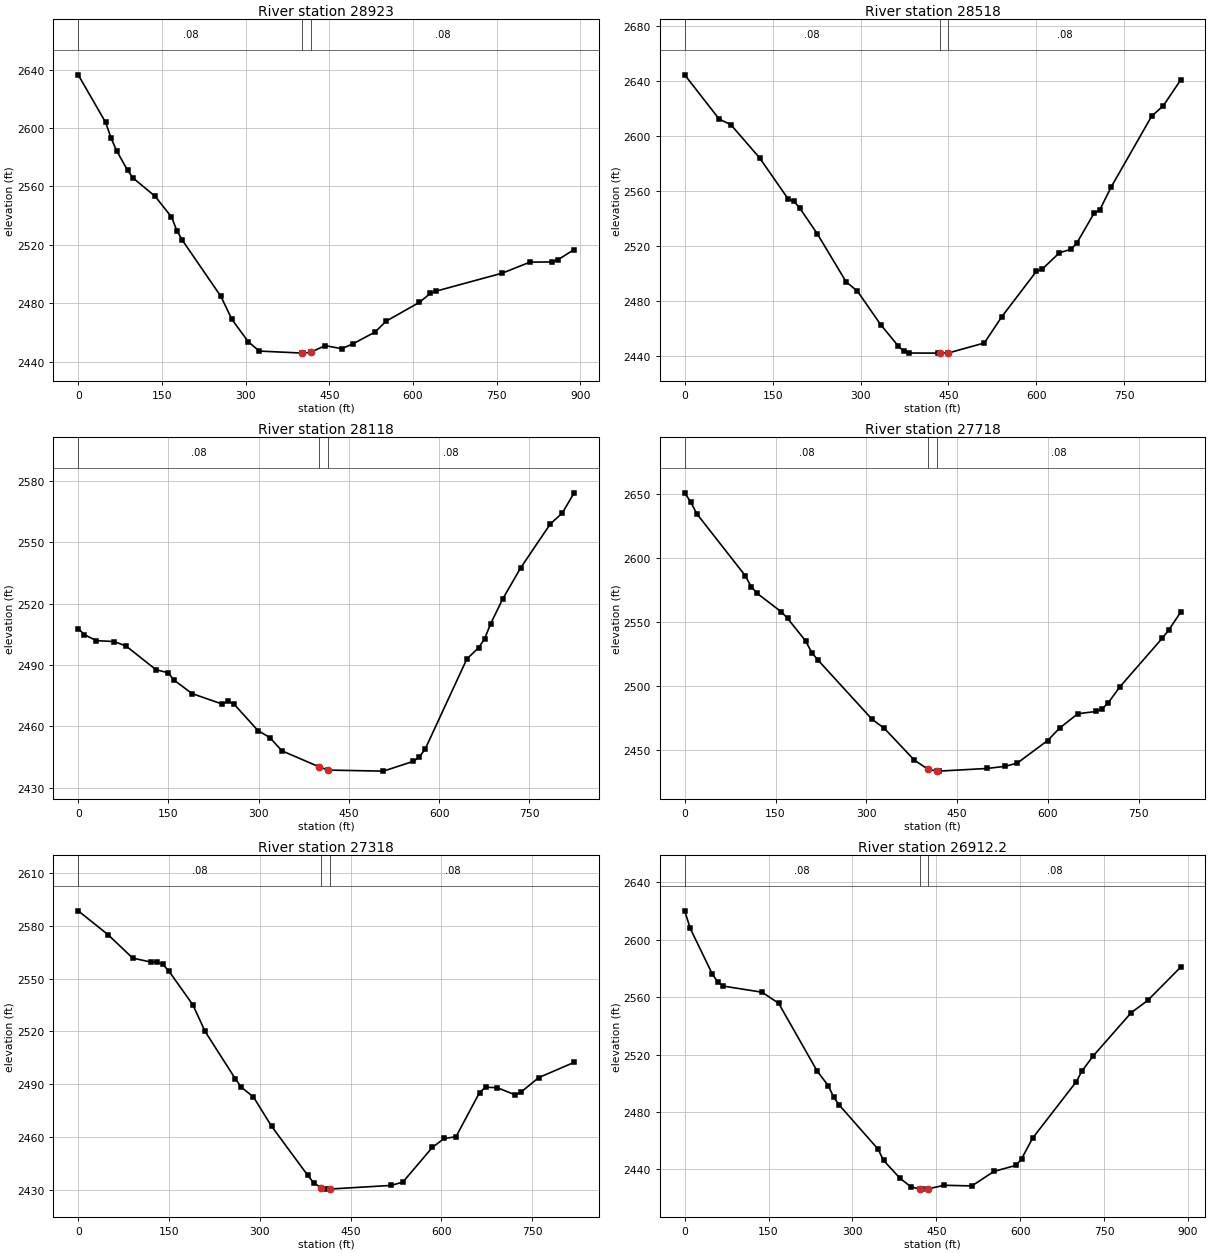
Type RM Length L Ch R = 1 ,28923   ,394.4,405,418.4
XS GIS Cut Line= 3
     1893110.014      172746.189     1892743.765      172480.368
     1892307.792      172459.508
#Sta/Elev= 30
       0 2636.38    49.2 2603.79      59 2592.97    68.9 2584.43    88.5    2571
    98.4 2565.74   137.7 2553.32   167.2 2539.15   177.1 2529.54   186.9 2523.09
   255.8 2484.75   275.5 2469.06     305 2453.65   324.6 2447.37     402 2445.98
   403.4 2445.96     417 2446.62   442.7 2451.08   472.4    2449   492.2 2452.28
   531.9 2460.34   551.8 2467.78   611.3 2480.64   631.1 2486.76     641 2488.32
   760.1 2500.68   809.7 2508.22   849.3 2508.35   859.3 2509.67     889 2516.85
#Mann= 3 , 0 , 0
       0     .08       0     402    .045       0     417     .08       0
Bank Sta=402,417
XS Rating Curve= 0 ,0
Exp/Cntr=0.3,0.1

Type RM Length L Ch R = 1 ,28518   ,403.9,400,391.2
XS GIS Cut Line= 3
     1893238.386      172620.028     1893047.559      172221.061
     1892919.892      171838.059
#Sta/Elev= 30
       0 2644.76      59 2612.48    78.6 2608.57   127.8 2584.35   176.9 2554.21
   186.7 2552.72   196.6 2547.62     226 2529.27   275.2 2494.29   294.8 2487.32
   334.2  2463.1   363.6 2447.84   373.5 2443.66   383.3 2442.38   432.4  2442.3
   434.8  2442.3   449.8 2442.41   511.2 2449.68   540.7 2468.63   599.8 2501.72
   609.6 2503.29   639.2 2515.29   658.9 2517.83   668.7 2522.21   698.3 2544.03
   708.1 2546.53   727.8 2563.34   796.7 2614.76   816.4  2622.2     846 2640.96
#Mann= 3 , 0 , 0
       0     .08       0   434.8    .045       0   449.8     .08       0
Bank Sta=434.8,449.8
XS Rating Curve= 0 ,0
Exp/Cntr=0.3,0.1

Type RM Length L Ch R = 1 ,28118   ,406.9,400,394.9
XS GIS Cut Line= 3
     1893647.349      172383.606       1893391.7      172065.253
     1893106.201      171762.241
#Sta/Elev= 30
       0 2507.78      10 2504.86    29.9 2501.88    59.8 2501.43    79.7 2499.22
   129.5 2487.62   149.4 2486.21   159.3 2482.61   189.2 2476.01     239 2470.92
     249 2472.22   258.9 2470.91   298.8 2457.93   318.7 2454.49   338.6 2448.04
   400.8 2440.16   415.8 2438.61   507.4  2438.1     557 2442.86   566.9 2444.87
   576.8 2448.82   646.2 2492.91     666  2498.5   675.9 2502.92   685.8 2510.17
   705.7 2522.18   735.4 2537.33     785 2558.91   804.8 2564.21   824.6 2574.12
#Mann= 3 , 0 , 0
       0     .08       0   400.8    .045       0   415.8     .08       0
Bank Sta=400.8,415.8
XS Rating Curve= 0 ,0
Exp/Cntr=0.3,0.1

Type RM Length L Ch R = 1 ,27718   ,396.8,400,401.8
XS GIS Cut Line= 3
       1893944.1      171960.617     1893603.377      171733.466
     1893262.653      171506.315
#Sta/Elev= 30
       0 2651.26      10 2644.08      20 2634.88    99.9  2586.6   109.9 2577.88
   119.8 2572.66   159.8 2558.17   169.8 2553.21   199.8 2535.48   209.7 2526.46
   219.7 2520.78   309.6 2474.23   329.6 2467.26   379.5 2442.25     402 2435.23
     417 2433.85   419.5 2433.78   499.4 2435.87   529.4 2437.54   549.3 2440.08
   599.3 2457.65   619.2 2467.43   649.2 2478.62   679.2 2480.39   689.2  2482.4
   699.2 2487.02   719.1 2499.88     789 2537.83     799 2543.74     819 2557.93
#Mann= 3 , 0 , 0
       0     .08       0     402    .045       0     417     .08       0
Bank Sta=402,417
XS Rating Curve= 0 ,0
Exp/Cntr=0.3,0.1

Type RM Length L Ch R = 1 ,27318   ,413.2,405.8,400
XS GIS Cut Line= 3
     1894152.594      171688.351     1893846.628      171416.382
     1893525.552      171161.015
#Sta/Elev= 30
       0 2588.48    49.9 2574.75    89.9 2561.64   119.8 2559.35   129.8 2559.58
   139.8 2557.99   149.8  2554.3   189.7  2534.9   209.7 2519.93   259.6 2493.03
   269.6 2488.21   289.6 2482.68   319.5 2466.08   379.4 2438.09   389.4 2433.77
   401.9 2430.98   409.4  2430.3   416.9 2430.37   516.8 2432.41   536.4 2434.24
   585.2    2454   604.7 2459.08   624.3 2460.07   663.3 2485.22   673.1 2488.21
   692.6 2487.96   721.9 2483.92   731.7 2485.43     761 2493.67   819.6 2502.35
#Mann= 3 , 0 , 0
       0     .08       0   401.9    .045       0   416.9     .08       0
Bank Sta=401.9,416.9
XS Rating Curve= 0 ,0
Exp/Cntr=0.3,0.1

Type RM Length L Ch R = 1 ,26912.2 ,393,394,394.8
XS GIS Cut Line= 3
     1894396.678      171221.092     1893842.735      170984.538
     1893577.119      170883.019
#Sta/Elev= 30
       0 2620.14     9.9 2607.91    49.4 2576.13    59.2 2570.47    69.1 2567.72
   138.2 2563.46   167.9 2555.78     237 2508.45   256.7 2498.38   266.6 2490.16
   276.5  2484.8   345.6 2454.21   355.5 2446.32   385.1 2433.82   404.8 2427.79
   420.1 2426.43   424.6 2426.29   435.1 2426.49   464.1 2428.97   513.5 2428.53
     553 2438.64   592.5 2442.85   602.3 2447.39     622 2461.76   700.4 2501.24
   710.2 2508.49   729.8 2518.79   798.4 2549.21   827.9 2557.73   886.7 2580.89
#Mann= 3 , 0 , 0
       0     .08       0   420.1    .045       0   435.1     .08       0
Bank Sta=420.1,435.1
XS Rating Curve= 0 ,0
Exp/Cntr=0.3,0.1

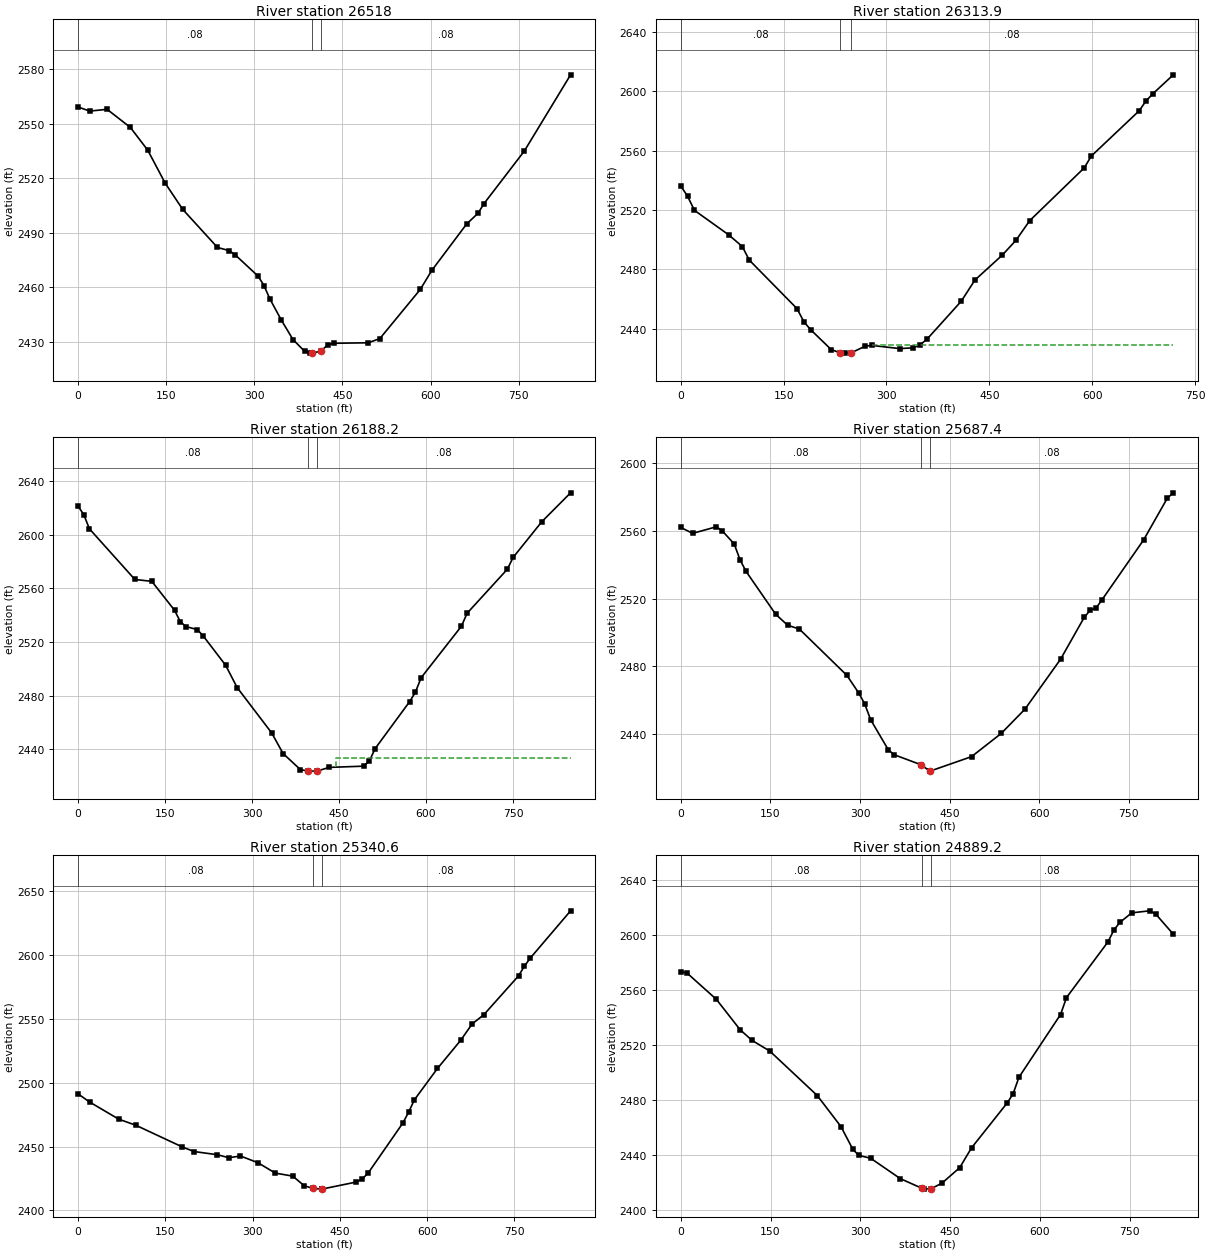
Type RM Length L Ch R = 1 ,26518   ,210.7,204.1,197.3
XS GIS Cut Line= 3
     1894585.617      170950.489     1894226.892      170761.688
     1893846.144      170555.754
#Sta/Elev= 30
       0 2559.22    19.8 2556.94    49.4 2557.92      89 2547.97   118.6 2535.45
   148.3  2517.3     178 2502.93   237.3 2481.93   257.1  2480.2     267 2478.01
   306.5 2466.13   316.4    2461   326.3 2453.73     346 2441.97   365.8 2431.26
   385.6 2424.81   395.5 2423.81   397.9 2423.84   412.9 2424.85     425 2428.34
   434.9 2429.23   493.9  2429.5   513.6  2431.8   582.5 2458.87   602.1 2469.34
   661.2 2494.79   680.8 2500.79   690.7 2505.98   759.5 2534.98   838.2 2576.89
#Mann= 3 , 0 , 0
       0     .08       0   397.9    .045       0   412.9     .08       0
Bank Sta=397.9,412.9
XS Rating Curve= 0 ,0
Exp/Cntr=0.3,0.1

Type RM Length L Ch R = 1 ,26313.9 ,129.5,125.7,121.9
XS GIS Cut Line= 2
     1894556.724      170628.473     1893852.122      170489.407
#Sta/Elev= 30
       0 2536.25      10 2529.19      20 2519.77    69.8 2503.34    89.8 2495.44
    99.8 2486.38   169.6 2453.63   179.6 2444.79   189.5 2439.46   219.4 2426.13
   232.7  2423.9   239.4 2423.75   247.7 2423.77   269.3 2428.52   279.3  2428.9
   319.2 2426.81   339.2 2427.32   349.1 2429.34   359.1 2433.14     409 2458.66
   428.9 2472.88   468.8 2489.67   488.8 2499.63   508.7  2512.8   588.5 2548.42
   598.5 2556.25   668.3 2586.69   678.3  2593.3   688.3 2598.17   718.2 2610.94
#Mann= 3 , 0 , 0
       0     .08       0   232.7    .045       0   247.7     .08       0
#XS Ineff= 2 , 0
                          279.26          2428.9
Permanent Ineff=
       F       F
Bank Sta=232.7,247.7
XS Rating Curve= 0 ,0
Exp/Cntr=0.3,0.1

Type RM Length L Ch R = 1 ,26188.2 ,483.8,500.7,517.4
XS GIS Cut Line= 3
     1894718.852      170458.867     1894464.361      170461.649
     1893869.854      170447.228
#Sta/Elev= 30
       0 2621.17     9.8    2615    19.6 2604.33    97.9 2566.61   127.2 2565.18
   166.4 2543.63   176.2 2535.22     186 2531.48   205.6 2529.24   215.4 2524.74
   254.5 2502.64   274.3 2486.05   333.8 2452.28   353.6 2436.84   383.4  2424.9
     397 2423.83     412 2423.77   432.9 2426.56   492.4 2427.47   502.3 2431.33
   512.2 2440.54   571.7 2475.56   581.6 2482.51   591.5 2493.36   660.9 2531.68
   670.8 2541.43   740.2 2574.23   750.1    2583   799.6 2609.62   849.2 2631.15
#Mann= 3 , 0 , 0
       0     .08       0     397    .045       0     412     .08       0
#XS Ineff= 2 , 0
                          445.45         2433.69
Permanent Ineff=
       F       F
Bank Sta=397,412
XS Rating Curve= 0 ,0
Exp/Cntr=0.3,0.1

Type RM Length L Ch R = 1 ,25687.4 ,346,346.8,347.9
XS GIS Cut Line= 2
     1894764.502      170319.737      1894156.45      169763.343
#Sta/Elev= 30
       0 2562.16    19.9 2558.66    59.6 2562.55    69.5 2560.12    89.4  2552.4
    99.3 2542.93   109.2 2536.19   158.9 2510.75   178.7 2504.36   198.6    2502
     278 2474.63   297.9 2464.17   307.8 2457.77   317.8 2448.36   347.6 2430.44
   357.5 2427.64   401.5 2421.82   416.5 2418.11   417.1 2417.98   486.6 2426.55
   536.2 2440.27     576 2454.66   635.5 2484.16   675.2 2508.98   685.2 2513.22
   695.1 2514.53     705  2519.4   774.6 2554.81   814.3 2579.53   824.2 2582.64
#Mann= 3 , 0 , 0
       0     .08       0   401.5    .045       0   416.5     .08       0
Bank Sta=401.5,416.5
XS Rating Curve= 0 ,0
Exp/Cntr=0.3,0.1

Type RM Length L Ch R = 1 ,25340.6 ,459.9,451.3,438.5
XS GIS Cut Line= 3
     1895010.829      170017.447     1894646.861      169790.843
     1894283.025       169585.49
#Sta/Elev= 30
       0 2491.28    19.9 2484.87    69.8 2471.48    99.7  2466.6   179.5  2449.6
   199.4 2446.07   239.3 2443.58   259.2 2441.23   279.2 2442.56   309.1 2437.33
     339 2429.17   368.9 2426.82   388.9 2419.23   403.5 2417.25   418.5 2416.62
   418.8 2416.61   478.5  2422.2   488.4  2424.6   498.4 2429.07   558.1 2468.33
     568 2476.78     578 2486.58   617.7 2511.18   657.5 2533.18   677.4 2546.13
   697.3 2553.25     757 2583.74     767 2591.23   776.9 2597.51   846.5 2634.74
#Mann= 3 , 0 , 0
       0     .08       0   403.5    .045       0   418.5     .08       0
Bank Sta=403.5,418.5
XS Rating Curve= 0 ,0
Exp/Cntr=0.3,0.1

Type RM Length L Ch R = 1 ,24889.2 ,297.1,294.8,292.5
XS GIS Cut Line= 2
     1895148.298      169460.065     1894332.956       169350.82
#Sta/Elev= 30
       0 2573.23     9.9 2572.61    59.5  2553.2    99.1  2531.1   118.9 2523.34
   148.7 2515.52     228  2483.1   267.6 2460.47   287.4 2443.91   297.3 2439.53
   317.2  2437.4   366.7 2422.56   403.4 2415.41   406.4 2414.92   418.4 2415.31
   436.1 2419.22   465.8 2430.52   485.6 2444.98   545.1 2477.68     555 2484.35
   564.9 2496.51   634.3 2542.15   644.2 2554.48   713.6 2595.14   723.5 2603.81
   733.4 2609.28   753.2 2616.25     783 2617.72   792.9 2615.53   822.6  2600.7
#Mann= 3 , 0 , 0
       0     .08       0   403.4    .045       0   418.4     .08       0
Bank Sta=403.4,418.4
XS Rating Curve= 0 ,0
Exp/Cntr=0.3,0.1

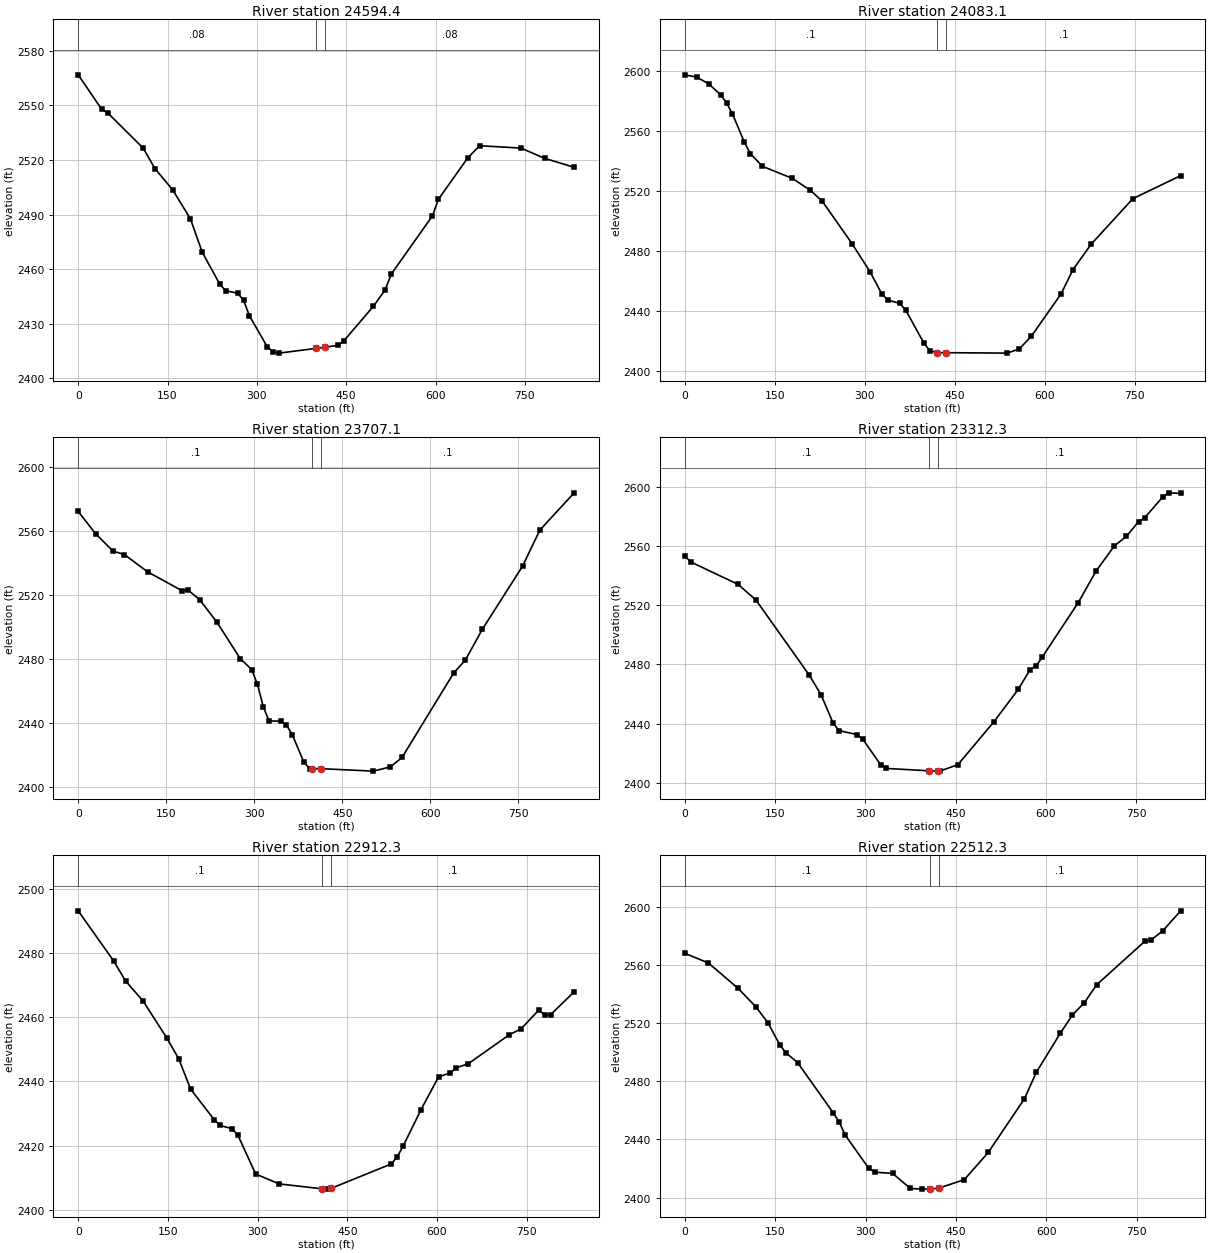
Type RM Length L Ch R = 1 ,24594.4 ,496.9,510.8,524.7
XS GIS Cut Line= 2
     1895183.664      169121.775      1894351.07      169110.024
#Sta/Elev= 30
       0 2566.83    39.6  2547.8    49.6 2545.88     109 2526.57   128.9 2515.27
   158.6  2503.6   188.3 2487.72   208.2 2469.36   237.9  2451.6   247.8 2448.13
   267.6 2446.79   277.6    2443   287.5 2434.35   317.2 2417.44   327.1 2414.53
     337 2413.84   399.6 2416.45   414.6 2417.06   436.2 2418.16   446.1 2420.62
   495.6 2439.58   515.5 2448.67   525.4 2457.17   594.8 2489.29   604.7 2498.39
   654.2 2521.24   674.1 2527.86   743.5 2526.55   783.1 2520.92   832.7    2516
#Mann= 3 , 0 , 0
       0     .08       0   399.6    .045       0   414.6     .08       0
Bank Sta=399.6,414.6
XS Rating Curve= 0 ,0
Exp/Cntr=0.3,0.1

Type RM Length L Ch R = 1 ,24083.1 ,364.8,376,387.1
XS GIS Cut Line= 2
     1895255.878      168912.092     1894579.669      168437.182
#Sta/Elev= 30
       0 2597.25    19.9 2595.73    39.8 2591.31    59.7 2584.06    69.7 2578.64
    79.6 2571.23    99.6 2552.22   109.5 2544.77   129.4 2536.33   179.2  2528.3
   209.1 2520.42     229  2513.2   278.8 2484.82   308.6 2466.23   328.5 2451.34
   338.5 2447.16   358.4 2445.04   368.4  2440.4   398.2 2418.82   408.2 2413.54
   420.8 2412.25   435.8 2412.18   537.6 2411.88   557.5 2414.69   577.4    2423
   627.2 2451.41   647.1 2467.56     677 2484.32   746.7 2514.76   826.3 2530.08
#Mann= 3 , 0 , 0
       0      .1       0   420.8    .045       0   435.8      .1       0
Bank Sta=420.8,435.8
XS Rating Curve= 0 ,0
Exp/Cntr=0.3,0.1

Type RM Length L Ch R = 1 ,23707.1 ,401.3,394.4,385.8
XS GIS Cut Line= 3
     1895369.918      168786.901      1895093.52      168264.374
     1894908.918      168090.208
#Sta/Elev= 30
       0 2572.06    29.6 2558.17    59.1 2547.33    78.8 2545.09   118.2 2534.34
   177.3 2522.46   187.2 2522.89   206.9 2516.97   236.4 2502.79   275.9 2480.16
   295.6 2473.25   305.4 2463.98   315.3 2450.01   325.1  2441.1   344.8 2441.02
   354.7 2438.62   364.5 2432.66   384.2 2415.62   394.1 2411.33   398.8 2411.27
   413.8  2411.3   502.5 2409.77     532 2412.44   551.7 2418.32   639.9 2471.23
   659.5 2479.15   688.7 2498.53   757.1 2537.95   786.4 2560.38   844.9 2583.71
#Mann= 3 , 0 , 0
       0      .1       0   398.8    .045       0   413.8      .1       0
Bank Sta=398.8,413.8
XS Rating Curve= 0 ,0
Exp/Cntr=0.3,0.1

Type RM Length L Ch R = 1 ,23312.3 ,399.8,399.9,398.5
XS GIS Cut Line= 3
     1895720.171      168413.716      1895413.73      168135.608
     1895092.905      167880.828
#Sta/Elev= 30
       0 2553.44     9.8  2549.4    88.7 2534.14   118.2 2523.65   206.9 2472.75
   226.6 2459.34   246.3 2440.46   256.2 2435.22   285.7 2432.56   295.6  2429.5
   325.2 2412.21     335 2409.62   406.3 2407.99   421.3  2407.8   423.8 2407.79
   453.8 2412.22   513.8 2441.34   553.7 2463.04   573.7 2476.52   583.7 2479.09
   593.7 2484.93   653.6 2521.86   683.6 2543.49   713.6 2560.24   733.6 2566.67
   753.6 2576.62   763.6 2579.12   793.5 2593.18   803.5 2596.11   823.5 2595.72
#Mann= 3 , 0 , 0
       0      .1       0   406.3    .045       0   421.3      .1       0
Bank Sta=406.3,421.3
XS Rating Curve= 0 ,0
Exp/Cntr=0.3,0.1

Type RM Length L Ch R = 1 ,22912.3 ,403.4,399.9,400.1
XS GIS Cut Line= 3
     1895994.915        168165.6     1895697.253      167875.911
     1895369.754      167622.548
#Sta/Elev= 30
       0 2493.11    59.3  2477.5    79.1  2471.3   108.8 2464.96   148.3 2453.47
   168.1 2447.05   187.9 2437.64   227.5 2428.06   237.4 2426.29   257.1 2425.29
     267 2423.29   296.7 2411.18   336.2 2408.09   407.9 2406.57   415.4 2406.47
   422.9 2406.71   523.8 2414.33   533.7 2416.59   543.5  2419.9   573.1 2431.14
   602.7 2441.43   622.4 2442.66   632.2 2444.24     652 2445.47     721 2454.53
   740.7 2456.38   770.3 2462.22   780.1 2460.69     790 2460.78   829.4 2467.89
#Mann= 3 , 0 , 0
       0      .1       0   407.9    .045       0   422.9      .1       0
Bank Sta=407.9,422.9
XS Rating Curve= 0 ,0
Exp/Cntr=0.3,0.1

Type RM Length L Ch R = 1 ,22512.3 ,417.3,421.5,424.8
XS GIS Cut Line= 3
      1896299.86      167884.559     1895974.096      167629.246
     1895662.762      167364.416
#Sta/Elev= 30
       0 2567.99    39.4 2561.25    88.7 2543.83   118.2 2531.09     138 2520.28
   157.7 2505.04   167.5 2499.71   187.2 2492.87   246.4 2458.29   256.2 2452.11
   266.1  2443.1   305.5 2420.02   315.4 2417.47   344.9 2416.65   374.5 2406.28
   394.2 2405.84   406.4 2405.92   421.4 2406.51   463.7 2412.34   503.6 2431.08
   563.4 2467.85   583.4 2486.25   623.2 2513.09   643.2 2525.58   663.1 2534.08
   683.1 2546.18   762.8 2576.05   772.8 2576.93   792.7 2583.22   822.6 2597.13
#Mann= 3 , 0 , 0
       0      .1       0   406.4    .045       0   421.4      .1       0
Bank Sta=406.4,421.4
XS Rating Curve= 0 ,0
Exp/Cntr=0.3,0.1

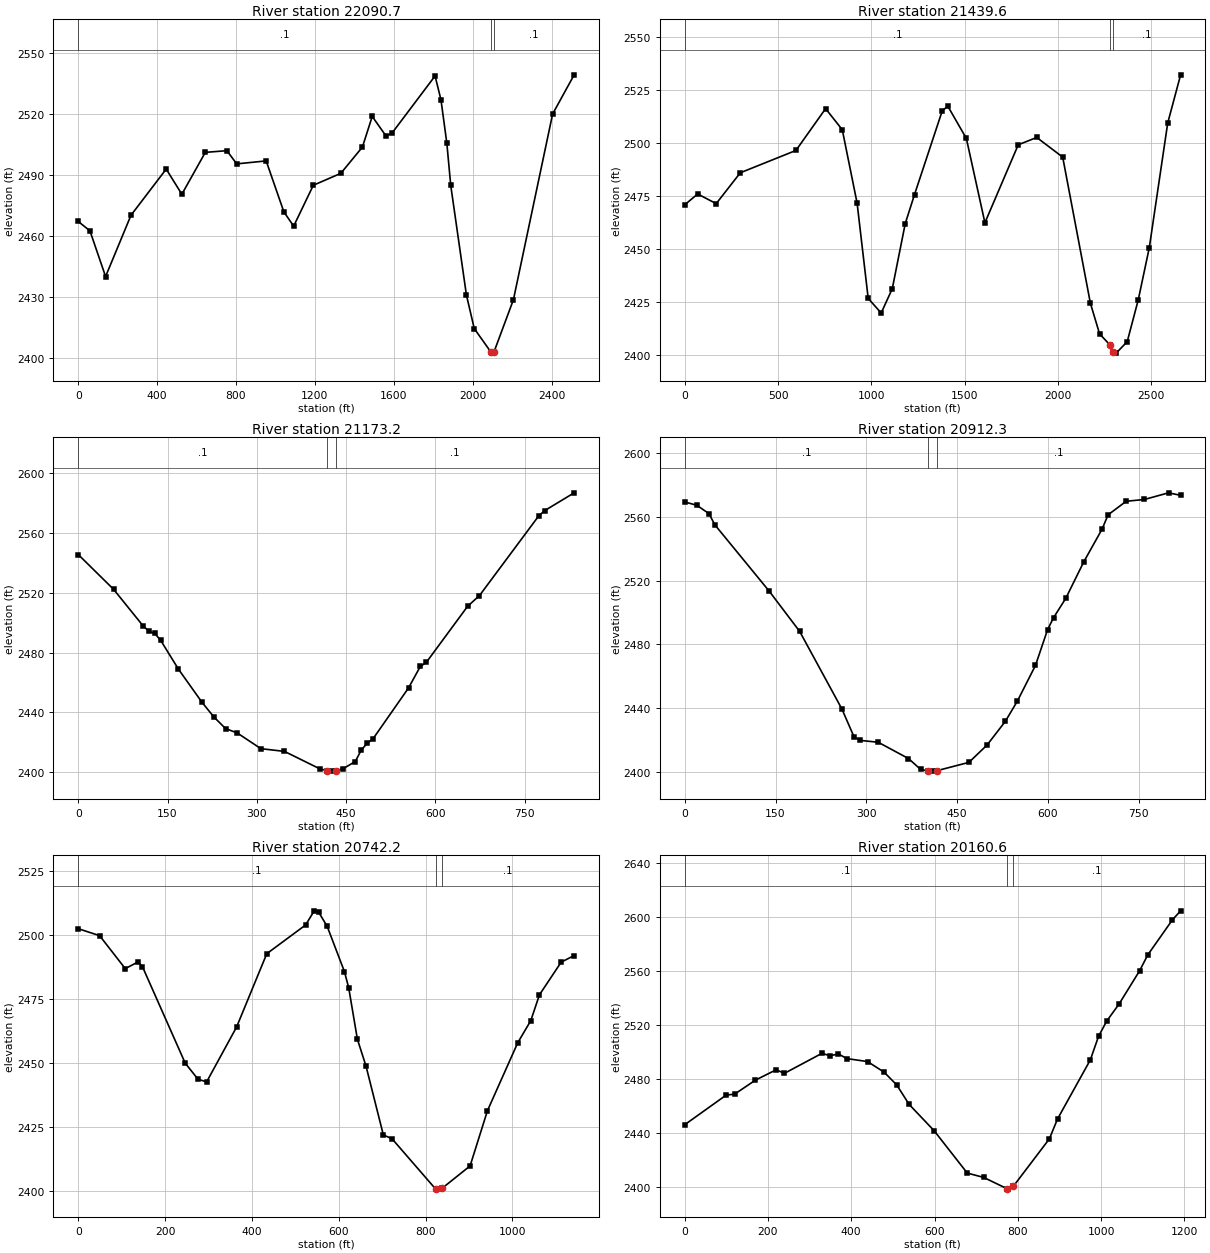
Type RM Length L Ch R = 1 ,22090.7 ,648.4,651,653.7
XS GIS Cut Line= 4
     1896965.969      169281.179     1896825.379      168611.635
     1896487.035      167580.039     1895993.492      167021.929
#Sta/Elev= 30
       0 2467.14    59.5 2462.52   138.8 2440.02   267.7 2470.21   446.2 2492.92
   525.5 2480.53   644.5 2501.15   753.9 2501.97   803.7 2495.48   953.1 2496.94
  1042.7 2471.89  1092.5 2464.82  1192.1 2484.95  1331.6 2490.82  1441.1 2503.75
  1490.9 2518.84  1560.6 2509.23  1590.5 2510.53  1809.5 2538.76  1839.4 2527.03
  1869.2 2505.68    1889 2484.88  1968.5 2430.92  2008.2 2414.43    2094 2402.67
  2097.6 2402.33    2109  2403.1  2206.9 2428.64  2405.6 2520.02  2514.8 2539.31
#Mann= 3 , 0 , 0
       0      .1       0    2094    .045       0    2109      .1       0
Bank Sta=2094,2109
XS Rating Curve= 0 ,0
Exp/Cntr=0.3,0.1

Type RM Length L Ch R = 1 ,21439.6 ,274.1,266.4,258
XS GIS Cut Line= 4
     1897206.605      169165.806     1897201.386      168361.143
     1896889.415      167119.505     1896555.786      166654.521
#Sta/Elev= 30
       0 2470.92    69.5 2476.06   168.9  2471.5     298 2486.07   596.1 2496.62
     755 2516.36   844.4  2506.4   923.8 2471.77   983.3 2426.73  1052.8 2419.85
  1112.3 2431.33  1181.8  2462.1  1231.4 2475.78  1380.3 2515.41  1410.1 2517.49
  1509.3 2502.26  1608.6 2462.46  1787.2 2499.29  1886.4 2502.75  2025.4 2493.47
  2173.7 2424.49    2223 2409.99  2279.4 2404.69  2294.4 2401.57  2311.8  2400.9
  2371.1 2406.32  2430.3 2426.09  2489.5 2450.77  2588.1 2509.58  2657.2 2532.33
#Mann= 3 , 0 , 0
       0      .1       0  2279.4    .045       0  2294.4      .1       0
Bank Sta=2279.4,2294.4
XS Rating Curve= 0 ,0
Exp/Cntr=0.3,0.1

Type RM Length L Ch R = 1 ,21173.2 ,258.2,260.8,264
XS GIS Cut Line= 3
     1897268.736      166996.305     1896931.194      166753.678
     1896582.316      166524.774
#Sta/Elev= 30
       0 2545.51    59.4 2522.25   108.9 2497.87   118.8 2494.17   128.7 2492.74
   138.6  2488.1   168.3 2468.93   207.8 2446.84   227.6  2437.1   247.4 2429.25
   267.2 2426.27   306.8 2415.81   346.4 2413.98   405.8 2402.34   418.5 2401.05
   425.6  2400.8   433.5 2401.08   445.5 2402.54   465.4 2407.23   475.3  2414.8
   485.2 2419.36   495.2 2422.41   554.8 2456.36   574.6 2470.73   584.6 2473.39
   654.1 2510.93     674 2518.09   773.4 2571.23   783.3 2574.77     833 2586.71
#Mann= 3 , 0 , 0
       0      .1       0   418.5    .045       0   433.5      .1       0
Bank Sta=418.5,433.5
XS Rating Curve= 0 ,0
Exp/Cntr=0.3,0.1

Type RM Length L Ch R = 1 ,20912.3 ,171,170.3,169.5
XS GIS Cut Line= 3
     1897408.433      166826.124     1897098.377      166558.624
     1896788.322      166291.125
#Sta/Elev= 30
       0 2569.47      20 2567.38      40 2562.16    49.9 2555.06   139.8 2513.34
   189.8 2488.22   259.7 2439.39   279.7  2421.9   289.6 2419.74   319.6 2418.55
   369.6 2408.32   389.5 2401.55     402  2400.5   409.5 2400.42     417 2400.74
   469.4 2405.92   499.4 2416.83   529.4 2431.61   549.3 2444.33   579.3  2466.8
   599.3 2489.28   609.3 2496.88   629.2 2508.83   659.2 2531.94   689.2 2552.32
   699.2 2561.36   729.1 2569.89   759.1    2571     799 2575.19     819 2573.63
#Mann= 3 , 0 , 0
       0      .1       0     402    .045       0     417      .1       0
Bank Sta=402,417
XS Rating Curve= 0 ,0
Exp/Cntr=0.3,0.1

Type RM Length L Ch R = 1 ,20742.2 ,581.2,581.4,581.6
XS GIS Cut Line= 4
     1897880.098      166911.491     1897581.202      166702.399
     1897328.777      166525.815     1896962.879      166231.612
#Sta/Elev= 30
       0 2502.46    49.3 2499.73   108.4 2486.83     138 2489.46   147.9 2487.62
   246.5 2449.83     276 2443.54   295.8 2442.52   364.8 2463.98   434.3 2492.67
   523.8 2503.92   543.6 2509.45   553.6 2508.99   573.5 2503.35   613.2 2485.66
   623.1 2479.28     643 2459.21   662.9 2448.69   702.8 2421.76   722.8 2420.26
   823.2 2400.59   832.7 2400.55   838.2 2400.89   902.6 2409.62   942.6 2431.24
  1012.5 2457.87  1042.4 2466.47  1062.4  2476.6  1112.4 2489.36  1142.3 2491.95
#Mann= 3 , 0 , 0
       0      .1       0   823.2    .045       0   838.2      .1       0
Bank Sta=823.2,838.2
XS Rating Curve= 0 ,0
Exp/Cntr=0.3,0.1

Type RM Length L Ch R = 1 ,20160.6 ,463.7,448.2,433.2
XS GIS Cut Line= 3
     1898050.685      166637.068     1897689.731      166085.747
     1897275.323       165751.93
#Sta/Elev= 30
       0 2446.37    99.8 2468.37   119.8    2469   169.7 2479.38   219.7 2487.09
   239.6 2484.45   329.5 2499.23   349.4  2497.5   369.4 2498.79   389.4 2495.38
   439.3 2493.15   479.2 2485.26   509.2 2475.89   539.2 2461.39   599.1 2441.95
   678.7 2410.59   718.1 2407.36   774.4 2398.99   777.2  2398.7   789.4 2400.81
   875.8  2435.9   895.5 2450.68   974.3 2494.44     994 2511.88  1013.7 2523.21
  1043.3  2535.8  1092.6 2560.41  1112.3 2572.21  1171.4 2598.12  1191.1  2604.8
#Mann= 3 , 0 , 0
       0      .1       0   774.4    .045       0   789.4      .1       0
Bank Sta=774.4,789.4
XS Rating Curve= 0 ,0
Exp/Cntr=0.3,0.1

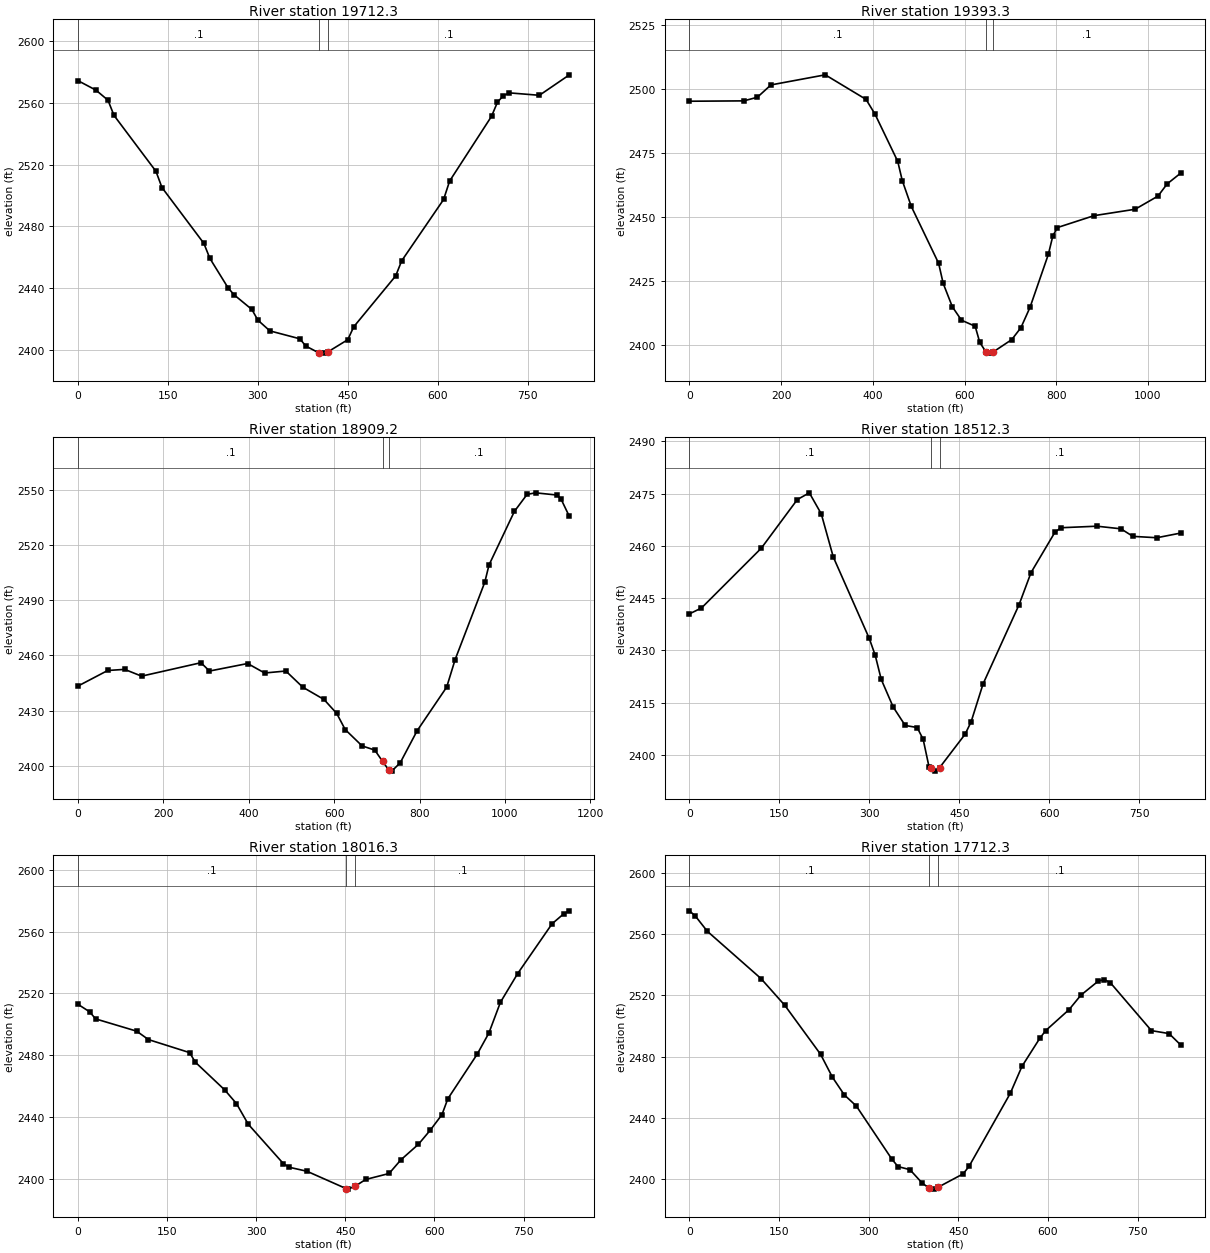
Type RM Length L Ch R = 1 ,19712.3 ,317.7,319.1,320
XS GIS Cut Line= 3
     1898119.236       165607.21     1897709.368      165605.805
     1897300.057      165597.281
#Sta/Elev= 30
       0 2574.12      30 2567.99      50  2561.5      60 2551.72     130 2515.61
     140 2505.15   209.9  2469.1   219.9 2459.42   249.9 2440.62   259.9 2436.04
   289.9 2426.46   299.9 2419.58   319.9 2412.64   369.9 2407.53   379.9 2402.82
   402.4  2398.3   409.9 2398.28   417.4 2399.26   449.8 2406.94   459.8 2415.29
   529.7 2448.13   539.7 2457.86   609.6 2497.43   619.6 2509.32   689.5 2551.11
   699.4 2560.23   709.4 2564.48   719.4 2566.23   769.3 2564.67   819.3 2577.88
#Mann= 3 , 0 , 0
       0      .1       0   402.4    .045       0   417.4      .1       0
Bank Sta=402.4,417.4
XS Rating Curve= 0 ,0
Exp/Cntr=0.3,0.1

Type RM Length L Ch R = 1 ,19393.3 ,477,483.9,490.9
XS GIS Cut Line= 3
     1898344.888      165438.008      1897850.43       165299.56
     1897293.342      165265.571
#Sta/Elev= 30
       0 2495.28   118.5 2495.42   148.1 2496.84   177.7 2501.66   296.2 2505.61
   385.1    2496   404.8 2490.18   454.2 2471.75   464.1 2464.24   483.8 2454.12
   543.4 2431.87   553.3 2424.02   573.3 2414.86   593.2 2409.61   623.1 2407.24
   633.1 2400.92   646.5 2397.22     653 2396.73   661.5 2397.08   702.8 2402.02
   722.8 2406.67   742.7 2414.65   782.6 2435.33   792.5 2442.62   802.5 2445.86
   882.2 2450.51   971.9 2453.02  1021.8 2458.18  1041.7 2462.93  1071.6  2467.2
#Mann= 3 , 0 , 0
       0      .1       0   646.5    .045       0   661.5      .1       0
Bank Sta=646.5,661.5
XS Rating Curve= 0 ,0
Exp/Cntr=0.3,0.1

Type RM Length L Ch R = 1 ,18909.2 ,411.7,396.9,382.2
XS GIS Cut Line= 3
     1898443.779      165279.781     1897978.989      164906.466
     1897464.111      164699.406
#Sta/Elev= 30
       0 2443.33    69.6 2451.78   109.3 2452.39     149 2448.71   288.1 2456.01
     308 2451.48   397.4 2455.57   437.2 2450.42   486.9  2451.5   526.6 2442.71
   576.3 2436.04   606.1 2428.46   625.9 2419.72   665.5 2410.83   695.2 2408.56
   713.4 2402.46   728.4 2397.61   734.9 2397.13   754.7  2401.6   794.4 2419.04
   863.7 2442.77   883.5 2457.74   952.9 2499.69   962.8 2509.07  1022.3 2538.19
    1052 2547.42  1071.8 2548.27  1121.4 2547.08  1131.3    2545  1151.1 2535.43
#Mann= 3 , 0 , 0
       0      .1       0   713.4    .045       0   728.4      .1       0
Bank Sta=713.4,728.4
XS Rating Curve= 0 ,0
Exp/Cntr=0.3,0.1

Type RM Length L Ch R = 1 ,18512.3 ,481.8,495.9,510.1
XS GIS Cut Line= 3
     1898254.964      164359.426      1897860.57      164469.625
     1897466.176      164579.824
#Sta/Elev= 30
       0 2440.46      20 2442.13   119.8 2459.32   179.8 2473.27   199.8  2475.2
   219.7 2469.16   239.7 2456.79   299.6 2433.44   309.6 2428.58   319.6 2421.66
   339.6  2413.7   359.6 2408.42   379.5 2407.83   389.5 2404.46   399.5 2396.37
     402  2396.1   409.5 2395.31     417 2396.33   459.4  2405.9   469.4 2409.45
   489.4 2420.36   549.3 2443.06   569.3  2452.3   609.3 2463.94   619.2 2465.18
   679.2 2465.62   719.1 2464.87   739.1  2462.7     779 2462.31     819 2463.66
#Mann= 3 , 0 , 0
       0      .1       0     402    .045       0     417      .1       0
Bank Sta=402,417
XS Rating Curve= 0 ,0
Exp/Cntr=0.3,0.1

Type RM Length L Ch R = 1 ,18016.3 ,295.4,303.9,310.1
XS GIS Cut Line= 3
     1898207.381       164148.87     1897553.756      163922.495
     1897427.669       163873.05
#Sta/Elev= 30
       0 2513.02    19.8 2508.11    29.6  2503.6    98.8 2495.66   118.6 2490.23
   187.8 2481.82   197.6  2475.6     247 2457.69   266.8 2448.87   286.6 2435.55
   345.9 2410.01   355.7 2407.73   385.4 2405.16   451.7  2393.9   454.6 2393.61
   466.7 2395.52   484.2 2399.84   523.7 2403.71   543.5 2412.51   573.1 2422.59
   592.9 2431.64   612.7 2441.72   622.5 2451.92     672 2480.78   691.7 2494.46
   711.1  2514.3   740.1 2532.84   798.1 2565.06   817.5 2571.42   827.2 2573.41
#Mann= 3 , 0 , 0
       0      .1       0   451.7    .045       0   466.7      .1       0
Bank Sta=451.7,466.7
XS Rating Curve= 0 ,0
Exp/Cntr=0.3,0.1

Type RM Length L Ch R = 1 ,17712.3 ,437.3,419.9,404.8
XS GIS Cut Line= 3
     1898278.877      164030.983     1897967.667      163765.878
      1897628.03       163530.25
#Sta/Elev= 30
       0  2575.1      10 2571.64    29.9 2561.77   119.6 2530.96   159.5 2513.48
   219.4 2481.53   239.3 2466.53   259.2 2455.02   279.2 2447.81     339 2412.97
     349 2408.29   368.9 2406.29   388.9 2397.75   401.3 2394.08   408.8 2393.59
   416.3 2394.89     458 2403.56   467.9  2408.5   536.8 2456.06   556.4  2473.7
     586 2491.84   595.8 2496.89   635.2 2510.68   654.9 2520.07   684.4 2529.39
   694.2 2530.24   704.1 2528.28     773 2496.96   802.5 2495.04   822.2 2487.52
#Mann= 3 , 0 , 0
       0      .1       0   401.3    .045       0   416.3      .1       0
Bank Sta=401.3,416.3
XS Rating Curve= 0 ,0
Exp/Cntr=0.3,0.1