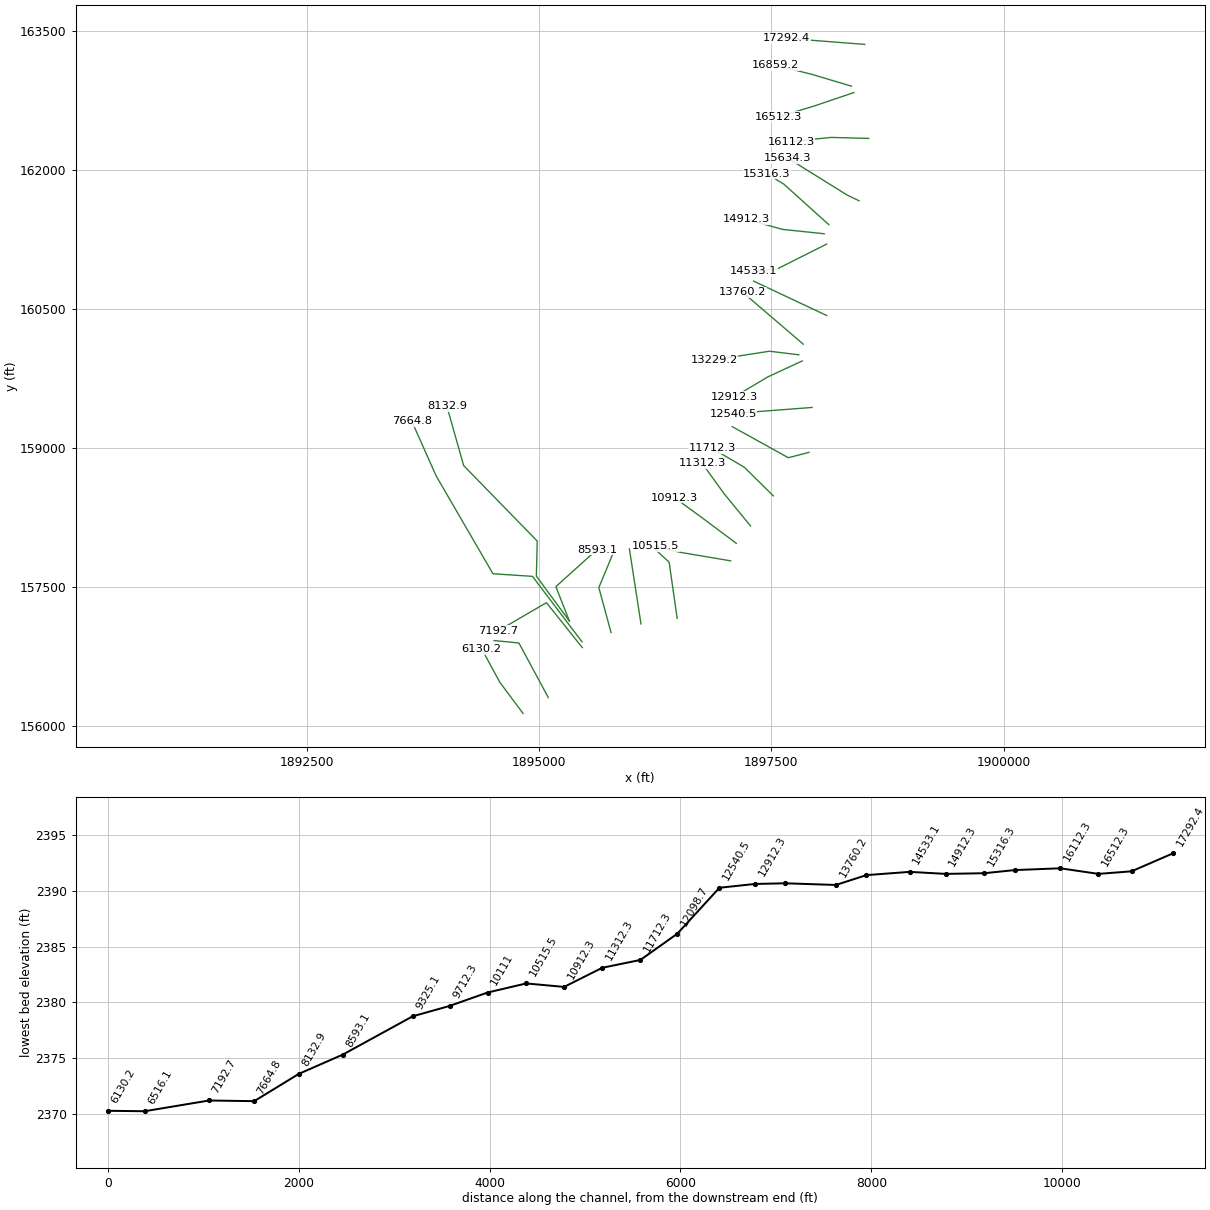
HEC-RAS study RghthndFrk.prj: RghthndFrk

--- RghthndFrk.g01 (geometry) --- (continued)

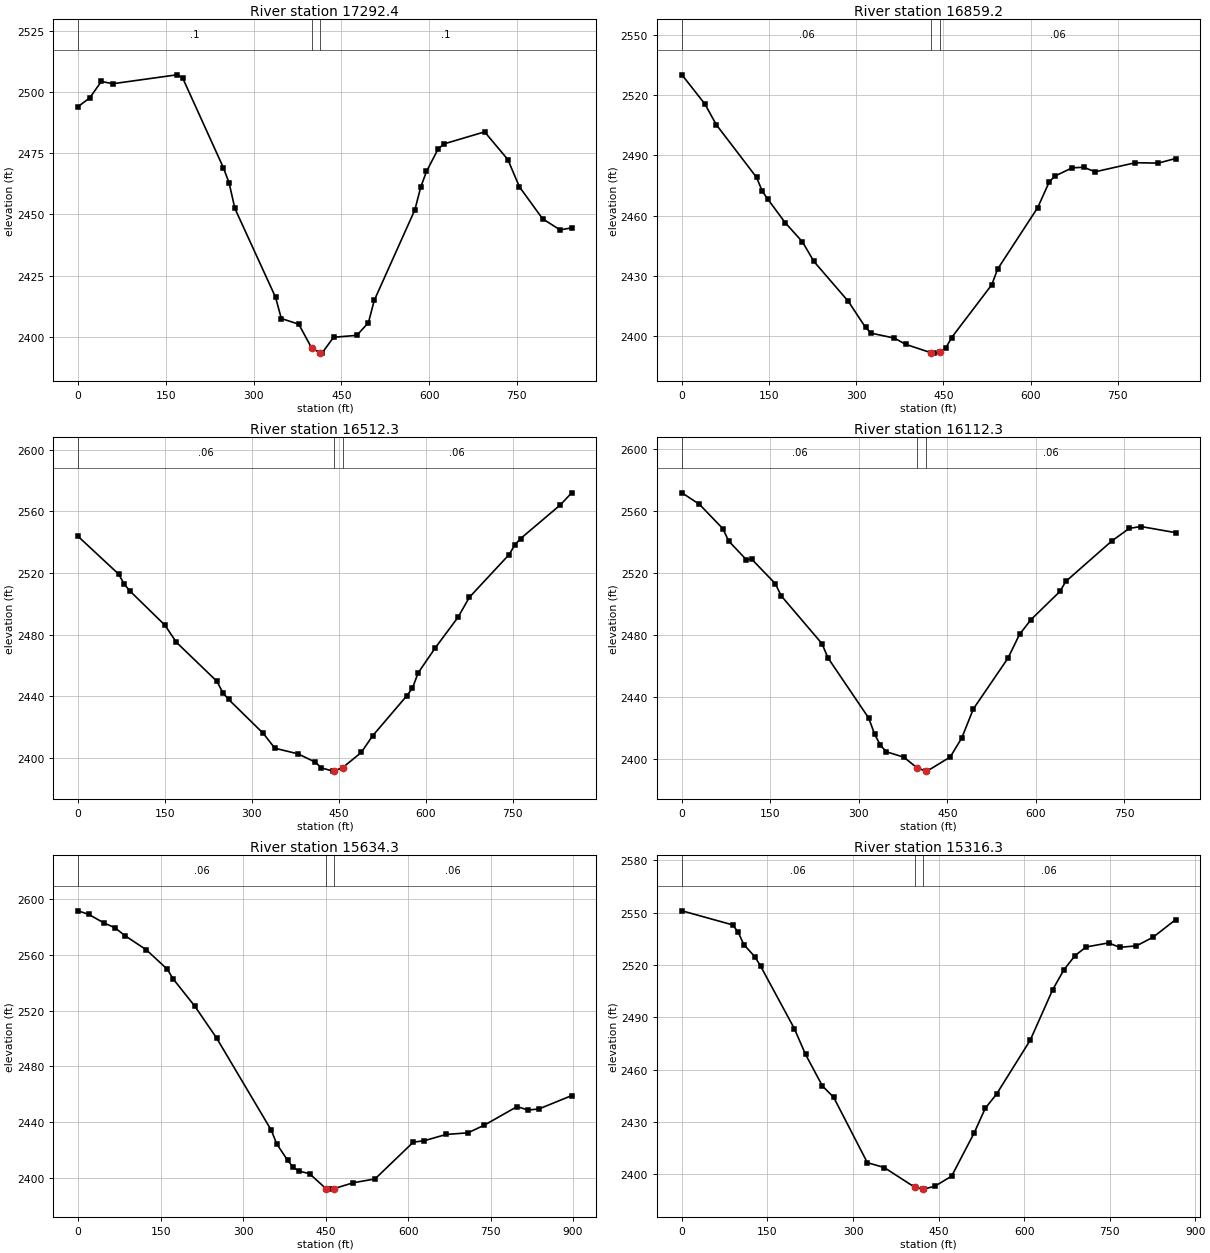
Type RM Length L Ch R = 1 ,17292.4 ,432.5,432.7,429.6
XS GIS Cut Line= 2
     1898505.115      163358.463     1897664.121        163423.8
#Sta/Elev= 30
       0 2494.12    19.8 2497.64    39.7 2504.38    59.5 2503.47   168.7  2507.1
   178.6 2505.87   248.1 2469.21     258 2462.98   267.9 2452.49   337.4 2416.18
   347.3 2407.46   377.1 2405.16   398.9  2395.5   413.9 2393.35   416.8 2393.32
   436.6 2399.81   476.4 2400.59   496.2 2405.81   506.1 2414.89   575.6 2451.94
   585.5 2461.17   595.4  2467.6   615.3 2476.79   625.2 2478.85   694.7 2483.78
   734.4 2472.46   754.2  2461.3   793.9 2448.22   823.7  2443.7   843.5 2444.55
#Mann= 3 , 0 , 0
       0      .1       0   398.9    .045       0   413.9      .1       0
Bank Sta=398.9,413.9
XS Rating Curve= 0 ,0
Exp/Cntr=0.3,0.1

Type RM Length L Ch R = 1 ,16859.2 ,335.4,346.7,359.9
XS GIS Cut Line= 3
     1898362.255      162907.324      1897936.62       163034.67
     1897543.866      163133.836
#Sta/Elev= 30
       0 2530.03    39.5  2515.5    59.2  2505.2   128.4 2479.04   138.2  2472.2
   148.1 2468.08   177.7 2456.52   207.3 2447.03   227.1 2437.27   286.3 2417.44
   315.9 2404.49   325.8 2401.62   365.3  2399.2     385 2396.09   429.4 2391.84
   434.4 2391.72   444.4 2392.16   454.2 2394.35     464 2399.43   533.2 2425.72
   543.1 2433.44   612.2 2464.04     632 2476.79   641.9 2479.73   671.5  2483.8
   691.3 2484.09     711 2481.83   780.2 2486.35   819.7 2486.16   849.4 2488.44
#Mann= 3 , 0 , 0
       0     .06       0   429.4    .045       0   444.4     .06       0
Bank Sta=429.4,444.4
XS Rating Curve= 0 ,0
Exp/Cntr=0.3,0.1

Type RM Length L Ch R = 1 ,16512.3 ,402.6,400,397.1
XS GIS Cut Line= 3
     1898386.966      162838.159      1897961.54      162693.494
     1897576.488      162576.689
#Sta/Elev= 30
       0 2543.74    69.9 2519.28    79.9 2512.62    89.9 2508.13   149.8 2486.17
   169.8 2474.98   239.6 2449.72   249.6 2442.44   259.6 2438.04   319.5 2415.98
   339.5 2406.35   379.4  2402.7   409.4 2397.29   419.4 2393.67   439.4 2391.49
   441.8 2391.62   456.8 2393.81   488.6  2403.6   508.2 2414.38   567.1  2440.3
   576.9 2445.32   586.8 2455.21   616.2 2471.38   655.4 2491.19   675.1 2504.19
   743.8 2531.96   753.6 2538.28   763.4 2542.28   832.1 2564.14   851.7 2571.99
#Mann= 3 , 0 , 0
       0     .06       0   441.8    .045       0   456.8     .06       0
Bank Sta=441.8,456.8
XS Rating Curve= 0 ,0
Exp/Cntr=0.3,0.1

Type RM Length L Ch R = 1 ,16112.3 ,489.6,477.8,463.1
XS GIS Cut Line= 3
     1898547.971      162343.465     1898142.401      162354.139
     1897713.706      162309.868
#Sta/Elev= 30
       0 2571.53    29.7 2564.09    69.3  2548.4    79.2 2540.44   108.8 2528.51
   118.7 2528.54   158.3 2512.89   168.2  2505.1   237.5 2474.15   247.4 2465.11
   316.6 2426.18   326.6 2415.79   336.4 2408.74   346.3 2404.48     376 2401.02
   398.2 2394.19   413.2 2392.03   415.5 2391.99   454.7  2401.1   474.3 2413.37
   493.9 2432.09   552.6 2464.85   572.2 2480.18   591.8 2489.79   640.8 2507.94
   650.6 2514.35   728.9 2540.55   758.3 2548.59   777.9 2549.79   836.7 2545.85
#Mann= 3 , 0 , 0
       0     .06       0   398.2    .045       0   413.2     .06       0
Bank Sta=398.2,413.2
XS Rating Curve= 0 ,0
Exp/Cntr=0.3,0.1

Type RM Length L Ch R = 1 ,15634.3 ,321.9,317.9,313.9
XS GIS Cut Line= 3
     1898443.779      161670.241      1898315.22      161732.048
     1897674.709      162131.515
#Sta/Elev= 30
       0 2591.84      19 2589.33    47.6 2583.01    66.6 2579.77    85.6 2573.88
   123.6 2563.98   162.5 2549.76   172.4 2543.11   212.2 2523.32   251.9 2500.38
   351.2 2434.22   361.2 2424.36     381 2412.51     391 2407.61   400.9 2404.86
   420.8 2402.94   450.6 2392.23   460.5 2391.83   465.6 2392.22   500.2  2396.4
   539.9 2399.15   609.5  2425.6   629.3  2426.6   669.1 2431.12   708.8 2432.28
   738.6 2437.78   798.2 2451.14     818 2448.67   837.9 2449.44   897.5 2459.05
#Mann= 3 , 0 , 0
       0     .06       0   450.6    .045       0   465.6     .06       0
Bank Sta=450.6,465.6
XS Rating Curve= 0 ,0
Exp/Cntr=0.3,0.1

Type RM Length L Ch R = 1 ,15316.3 ,389.4,403.7,414.3
XS GIS Cut Line= 3
     1898117.879      161412.479     1897635.341      161848.246
     1897452.392      161961.971
#Sta/Elev= 30
       0 2551.01    88.7 2542.97    98.5 2538.86   108.4 2531.71   128.1  2524.6
   137.9 2519.31     197 2483.58   216.7 2468.75   246.3 2450.67     266 2444.18
   325.1 2406.72   354.6 2403.94   407.8 2392.73   422.8  2391.6   423.6 2391.55
   443.3 2393.18   472.9 2398.98   512.3 2423.67     532 2437.93   551.7 2446.01
   610.8 2476.92   650.2 2505.87   669.8 2517.21   689.4 2525.39   708.9 2530.31
   748.1 2532.62   767.7 2530.08   797.1 2530.95   826.4 2535.93   865.6 2545.92
#Mann= 3 , 0 , 0
       0     .06       0   407.8    .045       0   422.8     .06       0
Bank Sta=407.8,422.8
XS Rating Curve= 0 ,0
Exp/Cntr=0.3,0.1

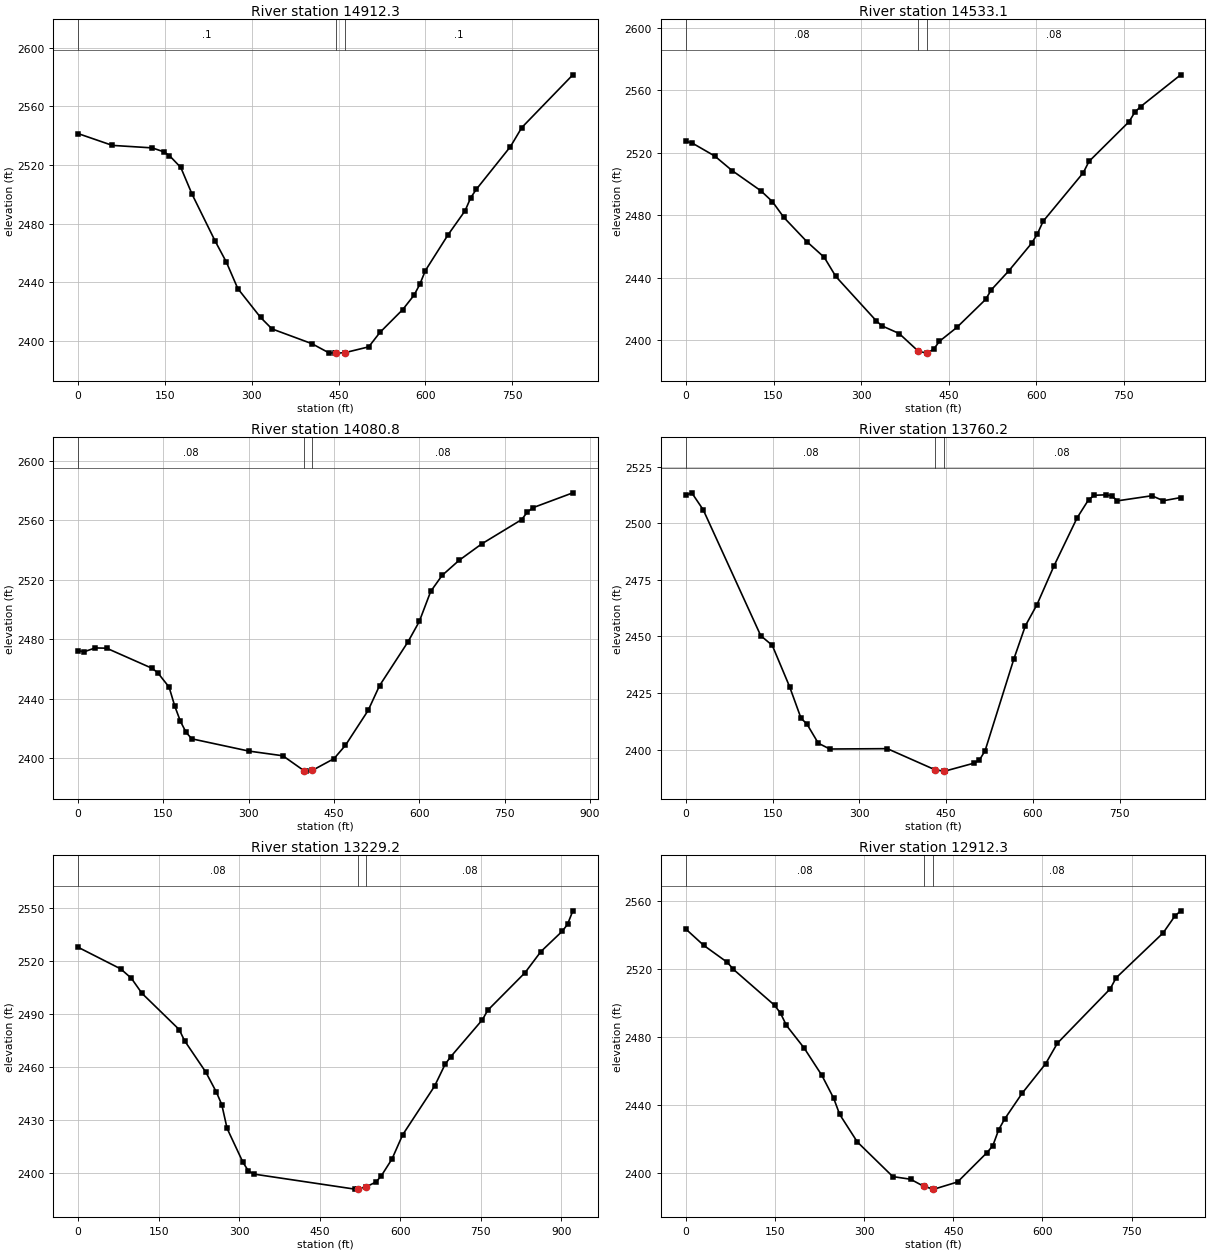
Type RM Length L Ch R = 1 ,14912.3 ,366.3,379.3,396.1
XS GIS Cut Line= 3
     1898068.475      161314.093     1897617.765      161361.714
     1897230.931      161470.299
#Sta/Elev= 30
       0 2541.45    59.1  2533.4   128.1 2531.69   147.8 2529.04   157.6 2526.47
   177.4 2518.32     197 2499.95   236.5 2468.24   256.2 2453.65   275.9 2435.61
   315.3 2415.87     335 2408.04     404 2397.95   433.5 2391.66   443.4 2391.49
   445.7 2391.49   460.7 2391.77   502.2 2395.78   521.8 2405.72     561 2421.25
   580.6 2431.11   590.4 2438.41   600.2 2447.92   639.4 2472.36   668.8 2488.77
   678.6 2497.74   688.4  2503.5   747.2 2532.58   766.8  2545.6     855  2581.6
#Mann= 3 , 0 , 0
       0      .1       0   445.7    .045       0   460.7      .1       0
Bank Sta=445.7,460.7
XS Rating Curve= 0 ,0
Exp/Cntr=0.3,0.1

Type RM Length L Ch R = 1 ,14533.1 ,473.2,452.2,431.2
XS GIS Cut Line= 3
     1898094.637      161202.739     1897566.117      160935.972
      1897312.27         160909.
#Sta/Elev= 30
       0 2527.32     9.9 2526.43    49.3 2517.93    78.9 2508.65   128.3 2495.67
     148 2488.74   167.7 2478.57   207.2 2463.03   236.8 2453.05   256.6 2440.78
   325.6 2412.48   335.5 2409.16   365.1 2404.24     398 2392.86     413 2391.67
   424.3 2394.24   434.2 2399.28   463.8  2408.1   513.1 2426.04     523 2432.25
   552.6 2444.26     592 2462.07   601.8 2468.02   611.7 2476.14   680.4 2507.21
   690.2 2514.48   758.9 2539.96   768.8 2546.08   778.6 2549.58   847.3 2569.98
#Mann= 3 , 0 , 0
       0     .08       0     398    .045       0     413     .08       0
Bank Sta=398,413
XS Rating Curve= 0 ,0
Exp/Cntr=0.3,0.1

Type RM Length L Ch R = 1 ,14080.8 ,326.9,320.5,314.6
XS GIS Cut Line= 2
     1898095.187      160431.625     1897308.673      160802.713
#Sta/Elev= 30
       0  2472.4      10 2471.52      30 2474.15      50 2473.98     130 2460.46
     140 2457.45   159.9 2447.81   169.9 2435.01   179.9 2424.77   189.9 2417.34
   199.9 2413.07   299.9 2404.86   359.9 2401.69   396.6  2391.8   399.8 2391.38
   411.6 2391.85   449.8 2399.77   469.8 2408.66   509.8 2432.15   529.8 2448.75
   579.8 2478.18   599.8 2491.94   619.8 2512.12   639.8 2522.85   669.7    2533
   709.7  2544.1   779.7 2560.36   789.7 2565.41   799.7 2568.39   869.7 2578.36
#Mann= 3 , 0 , 0
       0     .08       0   396.6    .045       0   411.6     .08       0
Bank Sta=396.6,411.6
XS Rating Curve= 0 ,0
Exp/Cntr=0.3,0.1

Type RM Length L Ch R = 1 ,13760.2 ,511.7,531,549.7
XS GIS Cut Line= 2
       1897842.4       160122.46     1897193.422      160680.003
#Sta/Elev= 30
       0 2512.41      10 2513.47    29.8 2505.96   129.3 2450.34   149.2 2446.08
   179.1 2427.87     199 2413.82   208.9 2411.42   228.8 2402.84   248.7 2400.27
   348.2 2400.43   430.8 2391.09   445.8 2390.52   447.7  2390.5   497.4 2393.97
   507.4 2395.35   517.3 2399.52   567.1 2440.08     587 2454.73   606.9 2463.98
   636.7  2481.3   676.5 2502.43   696.4 2510.46   706.4 2512.39   726.2 2512.59
   736.2 2512.15   746.2 2509.93   805.8 2512.18   825.7 2509.97   855.6 2511.38
#Mann= 3 , 0 , 0
       0     .08       0   430.8    .045       0   445.8     .08       0
Bank Sta=430.8,445.8
XS Rating Curve= 0 ,0
Exp/Cntr=0.3,0.1

Type RM Length L Ch R = 1 ,13229.2 ,310.3,316.9,325.9
XS GIS Cut Line= 3
     1897794.365      160007.324     1897479.587      160045.948
     1896882.178      159953.108
#Sta/Elev= 30
       0  2527.7    79.3 2515.45    99.1 2510.16   118.9 2501.61   188.3 2481.06
   198.2 2474.79   237.8 2456.99   257.7 2445.54   267.6 2438.54   277.5 2425.06
   307.2 2405.75   317.1 2401.04     327 2399.19   515.4 2390.65   521.4 2390.84
   536.4 2391.93     555 2394.68   564.9 2398.22   584.7 2407.68   604.6 2421.42
     664 2448.96   683.8 2461.43   693.8 2465.54   753.2 2486.64   763.1 2491.99
   832.5 2513.26   862.2 2525.27   901.9 2536.78   911.8 2540.68   921.7 2548.36
#Mann= 3 , 0 , 0
       0     .08       0   521.4    .045       0   536.4     .08       0
Bank Sta=521.4,536.4
XS Rating Curve= 0 ,0
Exp/Cntr=0.3,0.1

Type RM Length L Ch R = 1 ,12912.3 ,379.9,371.8,361.4
XS GIS Cut Line= 3
      1897831.14      159940.835     1897461.477      159768.817
     1897096.505      159551.324
#Sta/Elev= 30
       0 2543.31    29.8 2533.83    69.6 2523.83    79.6 2519.78   149.2 2498.58
   159.1 2493.95   169.1 2486.74   198.9 2473.47   228.7 2457.43   248.6 2443.95
   258.6 2434.53   288.4 2418.29   348.1 2397.94   377.9 2396.41   400.2 2392.23
   415.2  2390.7   417.6 2390.59   457.1  2394.8   506.5 2412.02   516.4 2416.09
   526.3 2425.51   536.2 2431.73   565.8 2446.94   605.3 2464.26   625.1 2476.33
     714 2508.28   723.9 2514.74     803  2541.1   822.7 2550.98   832.6 2554.11
#Mann= 3 , 0 , 0
       0     .08       0   400.2    .045       0   415.2     .08       0
Bank Sta=400.2,415.2
XS Rating Curve= 0 ,0
Exp/Cntr=0.3,0.1

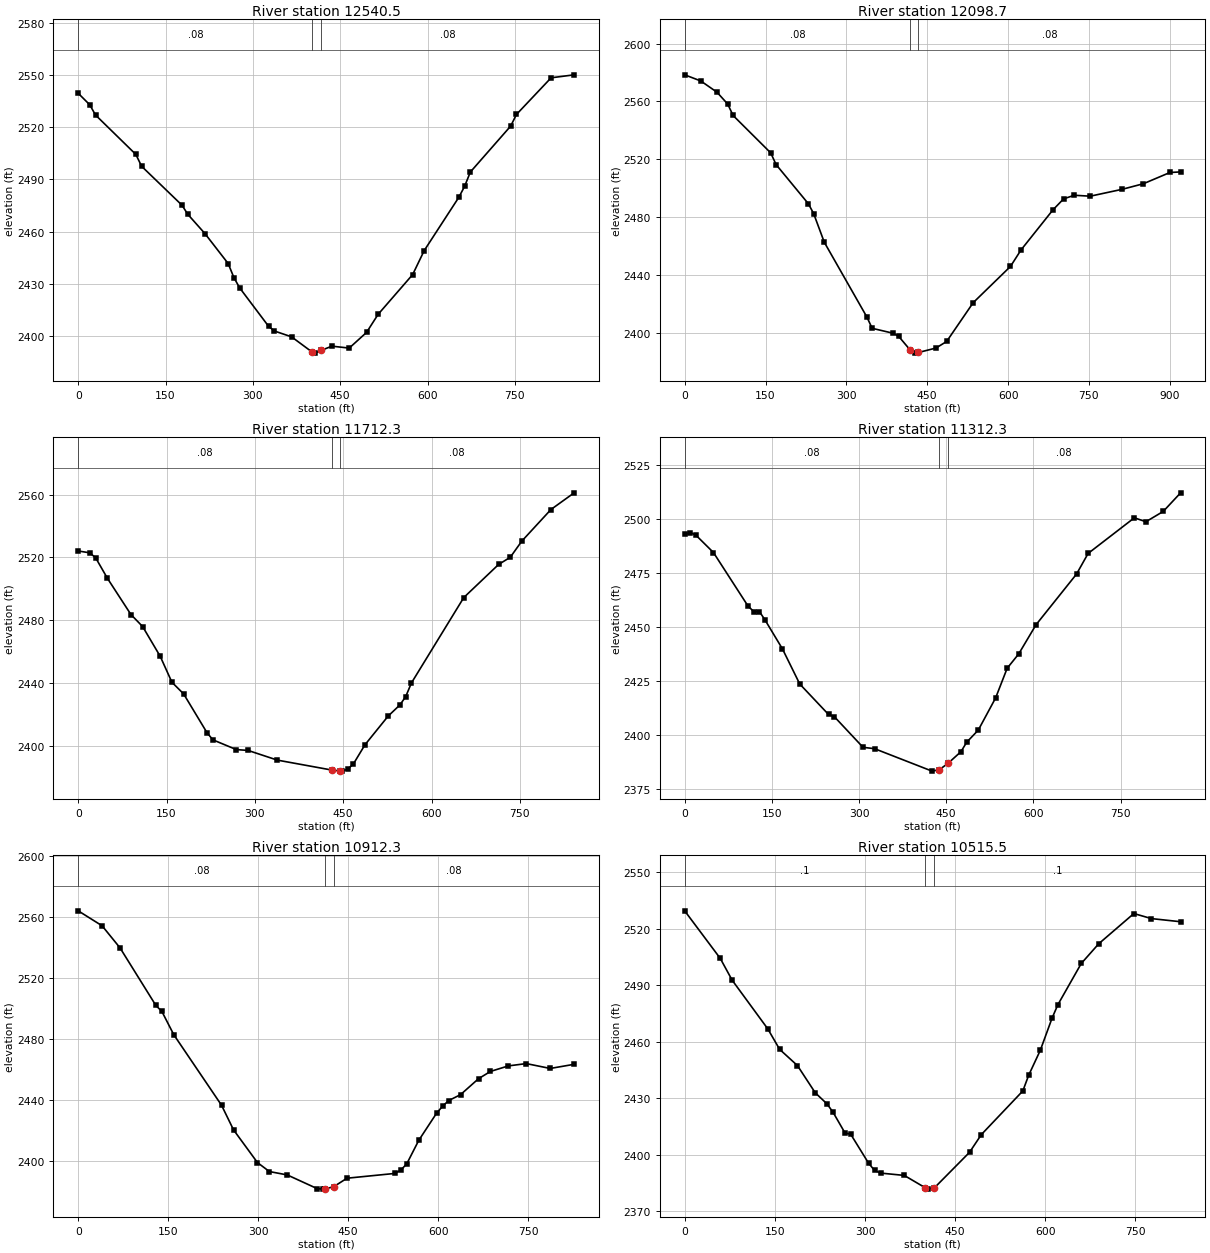
Type RM Length L Ch R = 1 ,12540.5 ,455.3,441.8,428.2
XS GIS Cut Line= 2
     1897938.101      159439.261     1897088.965      159373.486
#Sta/Elev= 30
       0 2539.51    19.8 2532.91    29.7 2527.03      99 2504.37   108.9 2497.57
   178.3 2475.19   188.2 2469.98   217.9 2458.81   257.5 2441.71   267.4 2433.63
   277.3 2427.72   326.8 2405.72   336.7 2402.98   366.4 2399.61   402.3 2390.72
     406 2390.25   417.3 2391.84   435.7 2394.25   465.4 2393.14   495.2 2402.16
     515 2412.52   574.4 2435.39   594.2 2449.16   653.6 2479.73   663.5 2485.99
   673.4 2494.26   742.7 2520.68   752.6 2527.34   812.1  2548.4   851.7 2550.11
#Mann= 3 , 0 , 0
       0     .08       0   402.3    .045       0   417.3     .08       0
Bank Sta=402.3,417.3
XS Rating Curve= 0 ,0
Exp/Cntr=0.3,0.1

Type RM Length L Ch R = 1 ,12098.7 ,392.8,386.2,385.5
XS GIS Cut Line= 3
     1897904.299       158954.41     1897682.314      158896.334
     1897078.631      159231.772
#Sta/Elev= 30
       0  2578.4    29.9 2574.16    59.9  2566.4    79.8 2558.22    89.8 2550.33
   159.6 2524.48   169.6 2516.39   229.5 2489.32   239.3 2482.51     259 2462.75
     338 2411.11   347.8 2403.29   387.3 2399.82   397.2 2397.65   418.7 2388.14
   426.8 2386.14   433.7 2386.58   466.2 2389.65     486 2394.19   535.3 2421.01
   604.4 2446.02   624.1 2457.48   683.3 2485.14     703  2492.7   722.8  2495.2
   752.4 2494.56   811.6 2499.31     851 2503.16   900.3 2510.93   920.1 2511.33
#Mann= 3 , 0 , 0
       0     .08       0   418.7    .045       0   433.7     .08       0
Bank Sta=418.7,433.7
XS Rating Curve= 0 ,0
Exp/Cntr=0.3,0.1

Type RM Length L Ch R = 1 ,11712.3 ,403.4,399.7,385.1
XS GIS Cut Line= 3
     1897520.107      158484.571     1897209.495      158792.791
     1896861.187      158998.553
#Sta/Elev= 30
       0 2524.09    19.9 2522.92    29.8 2519.63    49.7 2506.61    89.5 2483.61
   109.4 2475.92   139.2 2456.99   159.1 2440.45     179 2433.01   218.8 2408.22
   228.7 2403.74   268.5 2397.52   288.4 2396.99   338.1 2390.82   430.1 2384.52
   445.1 2383.85   447.4  2383.8   457.3 2384.96   467.2 2388.34   486.9 2400.59
   526.4 2418.93   546.1 2425.93     556 2431.22   565.8 2439.99   654.7 2494.42
   713.9 2515.54   733.6 2520.07   753.3 2530.42   802.7 2550.53   842.1 2561.16
#Mann= 3 , 0 , 0
       0     .08       0   430.1    .045       0   445.1     .08       0
Bank Sta=430.1,445.1
XS Rating Curve= 0 ,0
Exp/Cntr=0.3,0.1

Type RM Length L Ch R = 1 ,11312.3 ,397.5,399.9,405.4
XS GIS Cut Line= 3
     1897275.366       158160.17     1896993.187      158504.938
     1896754.665       158835.75
#Sta/Elev= 30
       0 2492.75     9.9 2493.62    19.8 2492.27    49.5 2484.36   108.9  2459.6
   118.8 2457.01   128.7 2456.99   138.6 2452.97   168.3 2439.68     198 2423.46
   247.5 2409.35   257.4 2408.35   306.9 2394.13   326.7  2393.5   425.7  2383.1
     438 2383.74     453 2386.66   475.4 2392.11   485.3 2396.49   505.2  2402.1
     535 2416.97   554.9 2430.74   574.8  2437.4   604.7 2450.94   674.3 2474.38
   694.2 2483.93   773.8 2500.44   793.7 2498.62   823.5  2503.4   853.4 2512.01
#Mann= 3 , 0 , 0
       0     .08       0     438    .045       0     453     .08       0
Bank Sta=438,453
XS Rating Curve= 0 ,0
Exp/Cntr=0.3,0.1

Type RM Length L Ch R = 1 ,10912.3 ,386,396.8,407.3
XS GIS Cut Line= 3
     1897122.213      157972.201     1896787.769       158223.17
     1896458.394      158464.531
#Sta/Elev= 30
       0 2564.09    39.8 2554.27    69.7 2539.76   129.4 2501.98   139.4 2498.05
   159.3 2482.75   238.9 2436.43   258.8 2420.33   298.7 2398.83   318.6 2392.93
   348.4 2390.71   398.2 2381.73   408.2 2381.39   410.6 2381.47   425.6 2382.94
     448 2388.56   527.7 2391.69   537.6 2393.86   547.6 2398.04   567.5 2413.39
   597.4 2431.34   607.4 2435.88   617.3  2439.5   637.2 2443.42   667.1 2453.87
     687 2458.65   716.9 2462.29   746.8  2463.8   786.6 2460.61   826.5 2463.33
#Mann= 3 , 0 , 0
       0     .08       0   410.6    .045       0   425.6     .08       0
Bank Sta=410.6,425.6
XS Rating Curve= 0 ,0
Exp/Cntr=0.3,0.1

Type RM Length L Ch R = 1 ,10515.5 ,433.3,404.4,375.6
XS GIS Cut Line= 3
     1897062.918      157782.803     1896517.867      157875.279
     1896253.332      157939.559
#Sta/Elev= 30
       0  2529.4    59.2 2504.15      79 2492.58   138.2 2466.78     158 2455.88
   187.6 2447.28   217.2 2432.85   236.9  2426.9   246.8 2422.52   266.6 2411.57
   276.4 2410.74     306 2395.45   315.9 2391.63   325.8 2390.22   365.3 2388.98
   400.5 2382.38   404.8  2381.7   415.5  2382.4   473.9 2401.23   493.6 2410.66
   562.6 2433.82   572.3 2442.13   591.7 2455.42   611.2 2472.44   620.9 2479.59
   659.8 2501.46     689 2511.96   747.3 2527.96   776.5 2525.28   825.1 2523.61
#Mann= 3 , 0 , 0
       0      .1       0   400.5    .045       0   415.5      .1       0
Bank Sta=400.5,415.5
XS Rating Curve= 0 ,0
Exp/Cntr=0.3,0.1

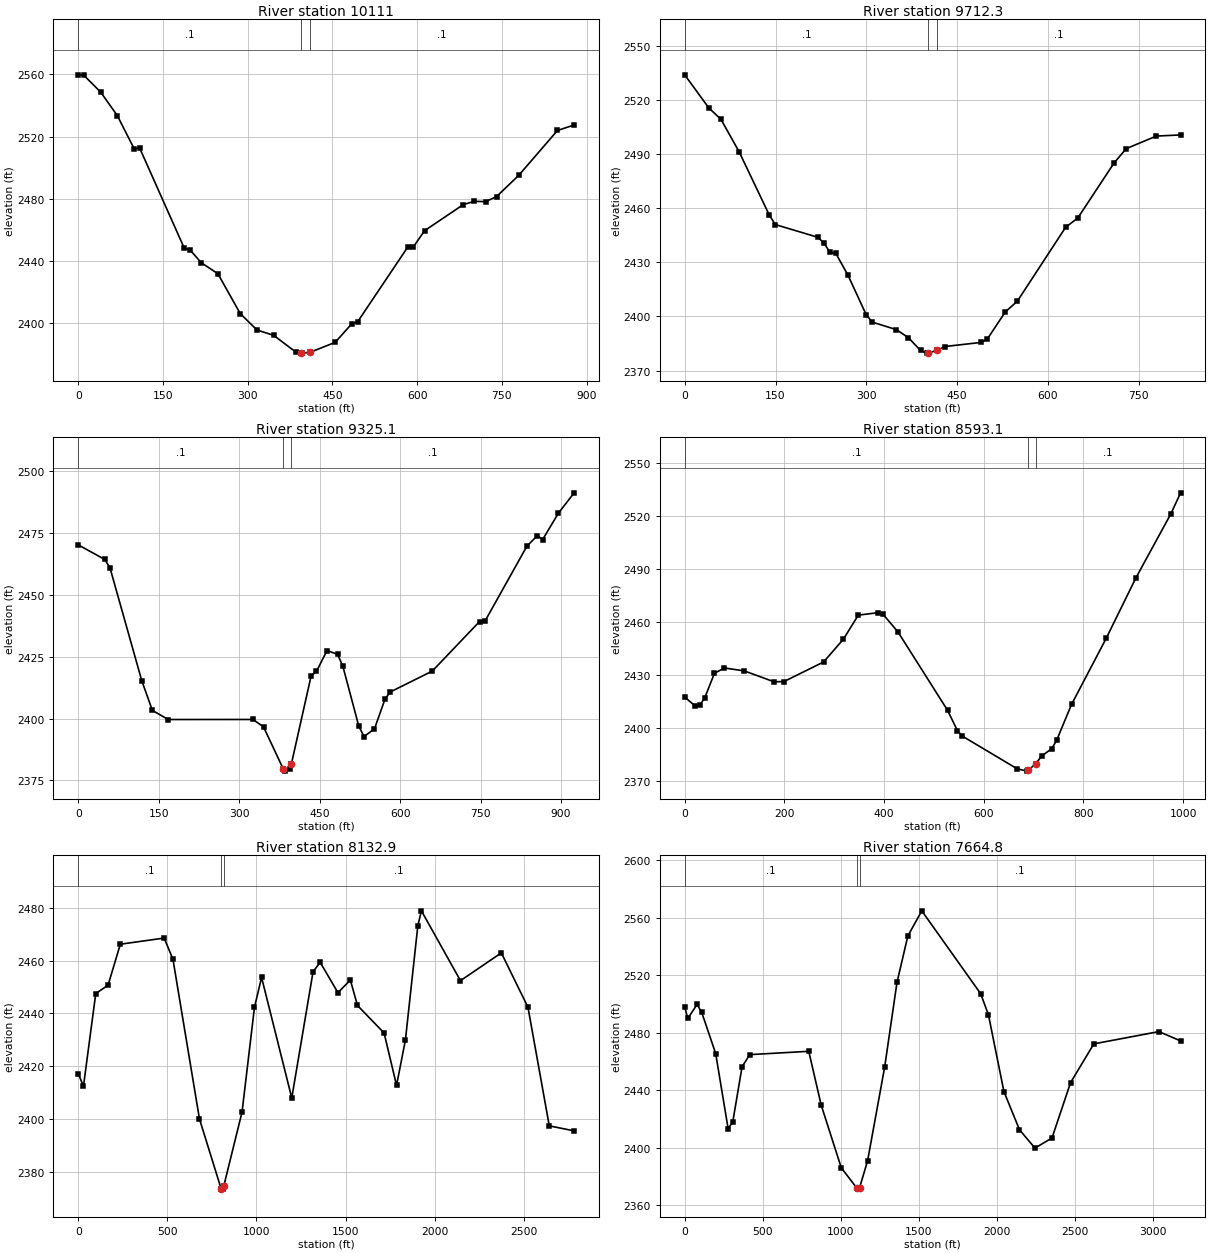
Type RM Length L Ch R = 1 ,10111   ,398.4,398.7,398.9
XS GIS Cut Line= 3
      1896485.56         157162.     1896399.197      157768.971
     1896204.077      157947.952
#Sta/Elev= 30
       0 2559.75     9.9 2559.48    39.6 2548.71    69.2 2533.56    98.9 2512.32
   108.8 2512.66   187.9 2448.21   197.8  2447.3   217.6 2439.05   247.2 2431.94
   286.8  2406.3   316.4 2395.77   346.1  2392.3   385.6 2381.44   395.2 2380.91
   395.5 2380.89   410.2 2381.37   454.9 2387.82   484.5 2399.84   494.4 2400.91
   583.4 2449.08   593.3 2449.17   613.1 2459.56   681.7 2476.35   701.3 2478.47
     721 2478.23   740.6 2481.51   779.8 2495.15   848.4 2523.99   877.9 2527.53
#Mann= 3 , 0 , 0
       0      .1       0   395.2    .045       0   410.2      .1       0
Bank Sta=395.2,410.2
XS Rating Curve= 0 ,0
Exp/Cntr=0.3,0.1

Type RM Length L Ch R = 1 ,9712.3  ,384.3,387.1,389.9
XS GIS Cut Line= 3
     1896096.202      157102.166     1896033.934      157506.905
     1895971.667      157911.643
#Sta/Elev= 30
       0 2533.79      40  2515.4    59.9 2509.16    89.9 2491.19   139.8 2456.08
   149.8 2450.86   219.7 2443.86   229.7  2440.8   239.7 2435.55   249.7 2434.86
   269.7 2422.81   299.6 2401.07   309.6 2396.88   349.6  2392.7   369.6 2388.21
   389.5 2381.15   399.5 2379.69     402 2379.75     417 2381.22   429.5 2383.34
   489.4 2385.62   499.4 2387.29   529.4 2402.47   549.3 2408.42   629.2 2449.42
   649.2  2454.5   709.1 2484.98   729.1  2492.9     779 2499.89     819  2500.5
#Mann= 3 , 0 , 0
       0      .1       0     402    .045       0     417      .1       0
Bank Sta=402,417
XS Rating Curve= 0 ,0
Exp/Cntr=0.3,0.1

Type RM Length L Ch R = 1 ,9325.1  ,757.8,731.9,706.5
XS GIS Cut Line= 3
     1895774.277      157008.736     1895642.677      157494.547
     1895803.834      157883.704
#Sta/Elev= 30
       0 2470.09    49.4 2464.21    59.2 2460.83   118.4 2415.32   138.2 2403.28
   167.8 2399.59   325.7 2399.61   345.4 2396.64   382.3 2379.62   384.9 2378.76
   394.8  2379.5   397.3 2381.58   434.2 2417.23   444.1 2418.99   463.8 2427.44
   483.6 2425.89   493.4 2421.03   522.9 2397.03   532.7 2392.71   552.3 2395.83
   571.9 2407.85   581.7 2410.71     660 2419.13   748.2 2439.15     758 2439.19
   836.4 2469.54     856 2473.84   865.8 2472.25   895.1 2482.86   924.5 2491.09
#Mann= 3 , 0 , 0
       0      .1       0   382.3    .045       0   397.3      .1       0
Bank Sta=382.3,397.3
XS Rating Curve= 0 ,0
Exp/Cntr=0.3,0.1

Type RM Length L Ch R = 1 ,8593.1  ,441.7,460.1,478.4
XS GIS Cut Line= 3
     1895325.334       157133.68     1895180.359      157504.436
     1895622.899      157904.947
#Sta/Elev= 30
       0 2417.28    19.9 2412.49    29.9 2412.67    39.8 2416.53    59.7 2430.72
    79.6 2433.75   119.4  2432.1   179.1 2425.94     199 2426.03   278.7 2437.14
   318.5 2450.06   348.3 2463.66   388.1 2465.05   398.1  2464.1   427.9 2454.16
   527.4 2409.78   547.3 2398.22   557.3 2395.12   666.7 2376.72   686.6 2375.34
   689.2 2375.77   704.2 2379.54   716.4 2383.93   736.3 2388.02   746.3 2392.81
   776.1 2413.08   845.7 2450.53   905.4 2484.82   975.1 2520.85     995 2532.91
#Mann= 3 , 0 , 0
       0      .1       0   689.2    .045       0   704.2      .1       0
Bank Sta=689.2,704.2
XS Rating Curve= 0 ,0
Exp/Cntr=0.3,0.1

Type RM Length L Ch R = 1 ,8132.9  ,432.7,468,503.3
XS GIS Cut Line= 5
     1895325.334       157133.68     1894970.215      157618.161
     1894979.866       157996.49     1894187.942       158811.04
      1894006.64      159453.835
#Sta/Elev= 30
       0 2417.28    29.5 2412.52    98.5 2447.53   167.4 2450.67   236.3 2466.16
   482.5 2468.49   531.8 2460.41   680.4 2400.15   801.6 2373.85   809.8 2373.62
   816.6 2374.73   919.4 2402.74   989.1 2442.32    1029 2453.62  1198.4 2408.06
    1318 2455.78  1357.8 2459.33  1457.5 2447.86  1527.2 2452.63  1567.1 2443.03
  1716.6  2432.6  1786.4 2412.82  1836.2 2429.95  1905.9 2473.13  1925.9 2478.78
  2145.1 2452.39  2374.4 2462.89  2523.9 2442.35  2643.5 2397.53  2783.1 2395.63
#Mann= 3 , 0 , 0
       0      .1       0   801.6    .045       0   816.6      .1       0
Bank Sta=801.6,816.6
XS Rating Curve= 0 ,0
Exp/Cntr=0.3,0.1

Type RM Length L Ch R = 1 ,7664.8  ,459.2,471.9,483.8
XS GIS Cut Line= 5
     1895460.698      156910.143     1894928.186      157615.689
     1894503.154      157643.495     1893891.734      158700.128
     1893629.754      159289.565
#Sta/Elev= 30
       0 2497.96    19.9 2489.81    79.5 2499.59   109.2 2494.02   198.6  2465.4
   278.1  2413.3   307.9 2417.88   367.5 2456.28   417.1 2464.69   794.6    2467
     874 2429.63  1002.8 2386.01  1104.5 2371.63  1111.8 2371.18  1119.5 2371.99
  1171.2 2390.87  1280.2 2455.77  1359.5  2514.9    1429 2547.16  1518.3 2564.66
  1895.5 2507.01  1945.1 2492.36  2044.3 2439.01  2143.6 2412.52  2242.8 2399.71
    2352 2406.73  2471.1 2445.24    2620 2472.17  3036.8  2480.7  3175.7  2474.2
#Mann= 3 , 0 , 0
       0      .1       0  1104.5    .045       0  1119.5      .1       0
Bank Sta=1104.5,1119.5
XS Rating Curve= 0 ,0
Exp/Cntr=0.3,0.1

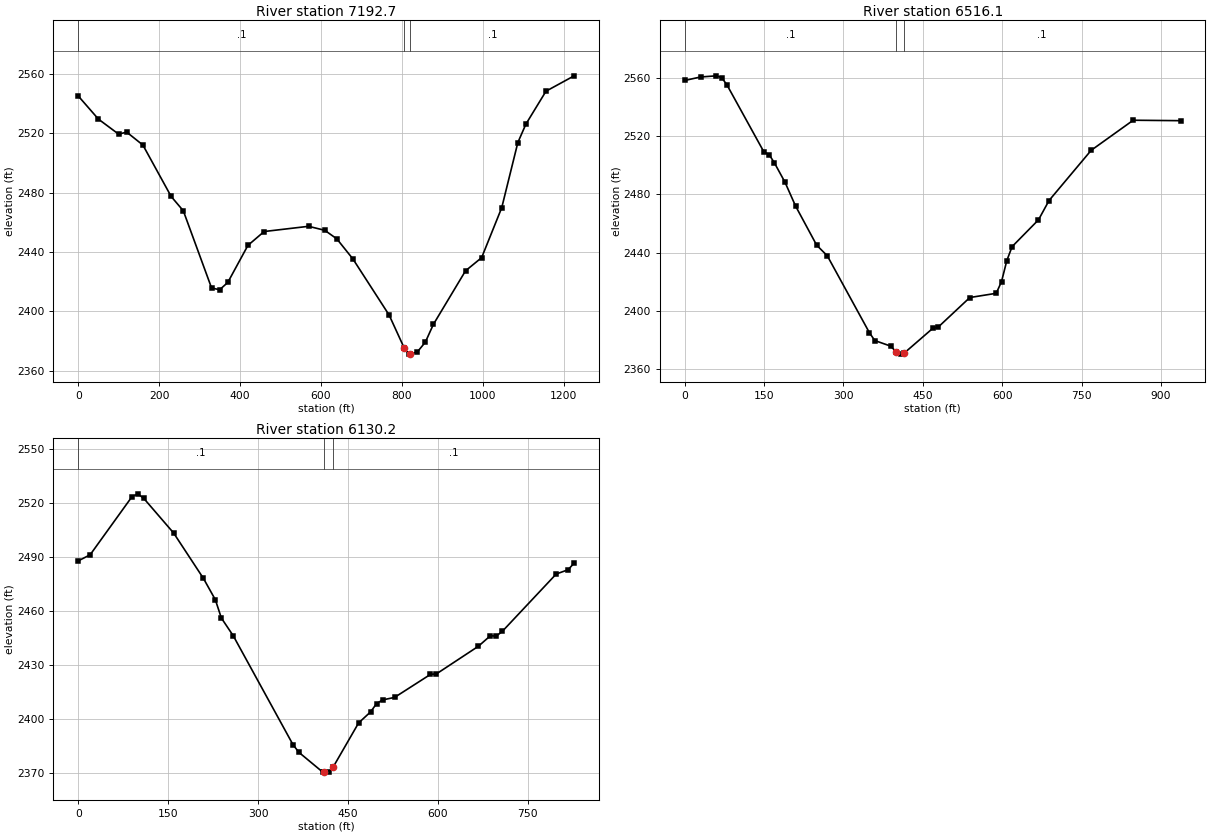
Type RM Length L Ch R = 1 ,7192.7  ,713.5,676.7,639.8
XS GIS Cut Line= 3
      1895464.48      156846.485     1895078.995      157331.376
     1894555.113      157025.701
#Sta/Elev= 30
       0 2545.23      50  2529.6    99.9 2519.48   119.9 2520.85   159.9 2512.14
   229.8 2477.47   259.8 2467.84   329.7  2415.8   349.7 2414.65   369.7 2419.53
   419.6 2444.54   459.6 2453.86   569.5 2457.38   609.5 2454.69   639.3 2448.92
   679.1 2435.37   768.6 2397.58   806.1 2375.24   818.3 2371.24   821.1 2371.26
   838.2 2372.67   858.1  2379.3     878 2391.28   957.5 2427.39   997.3 2436.26
    1047 2469.94  1086.8 2513.83  1106.7 2526.23  1156.4 2548.43    1226 2558.79
#Mann= 3 , 0 , 0
       0      .1       0   806.1    .045       0   821.1      .1       0
Bank Sta=806.1,821.1
XS Rating Curve= 0 ,0
Exp/Cntr=0.3,0.1

Type RM Length L Ch R = 1 ,6516.1  ,382.4,385.8,385.9
XS GIS Cut Line= 3
     1895098.731      156307.197     1894782.321      156896.253
     1894514.986      156922.602
#Sta/Elev= 30
       0 2558.07    29.9 2560.46    59.9 2561.26    69.9 2560.05    79.8  2555.1
   149.7 2509.05   159.7 2507.14   169.7 2501.46   189.6 2488.23   209.6 2471.89
   249.5 2445.02   269.5 2437.78   349.3 2384.88   359.3  2379.6   389.2 2375.79
   399.2 2372.04   409.2 2370.28   414.2 2370.78   469.1 2388.04     479 2388.77
   538.9 2409.12   588.8 2412.02   598.8 2420.02   608.8 2434.44   618.8 2444.04
   668.7 2462.46   688.6 2475.68   768.2 2510.13   847.7 2530.79   937.3 2530.48
#Mann= 3 , 0 , 0
       0      .1       0   399.2    .045       0   414.2      .1       0
Bank Sta=399.2,414.2
XS Rating Curve= 0 ,0
Exp/Cntr=0.3,0.1

Type RM Length L Ch R = 1 ,6130.2  ,385.8,399.9,417.4
XS GIS Cut Line= 3
     1894826.614      156136.447     1894577.275      156471.821
     1894382.181      156831.894
#Sta/Elev= 30
       0 2487.72    19.9 2491.11    89.6 2523.35    99.5 2524.99   109.4 2522.45
   159.2 2503.21     209 2477.94   228.8 2466.12   238.8 2455.97   258.7 2446.08
   358.2 2385.66   368.2 2381.31     408 2370.32   410.4 2370.33   417.9 2370.36
   425.4 2373.18   467.8 2397.66   487.8 2403.81   497.8 2408.42   507.8 2410.45
   527.8 2411.85   587.7 2424.64   597.7 2424.93   667.6 2440.27   687.6  2446.1
   697.6 2445.96   707.6 2448.57   797.5 2480.43   817.4 2482.81   827.4 2486.54
#Mann= 3 , 0 , 0
       0      .1       0   410.4    .045       0   425.4      .1       0
Bank Sta=410.4,425.4
XS Rating Curve= 0 ,0
Exp/Cntr=0.3,0.1