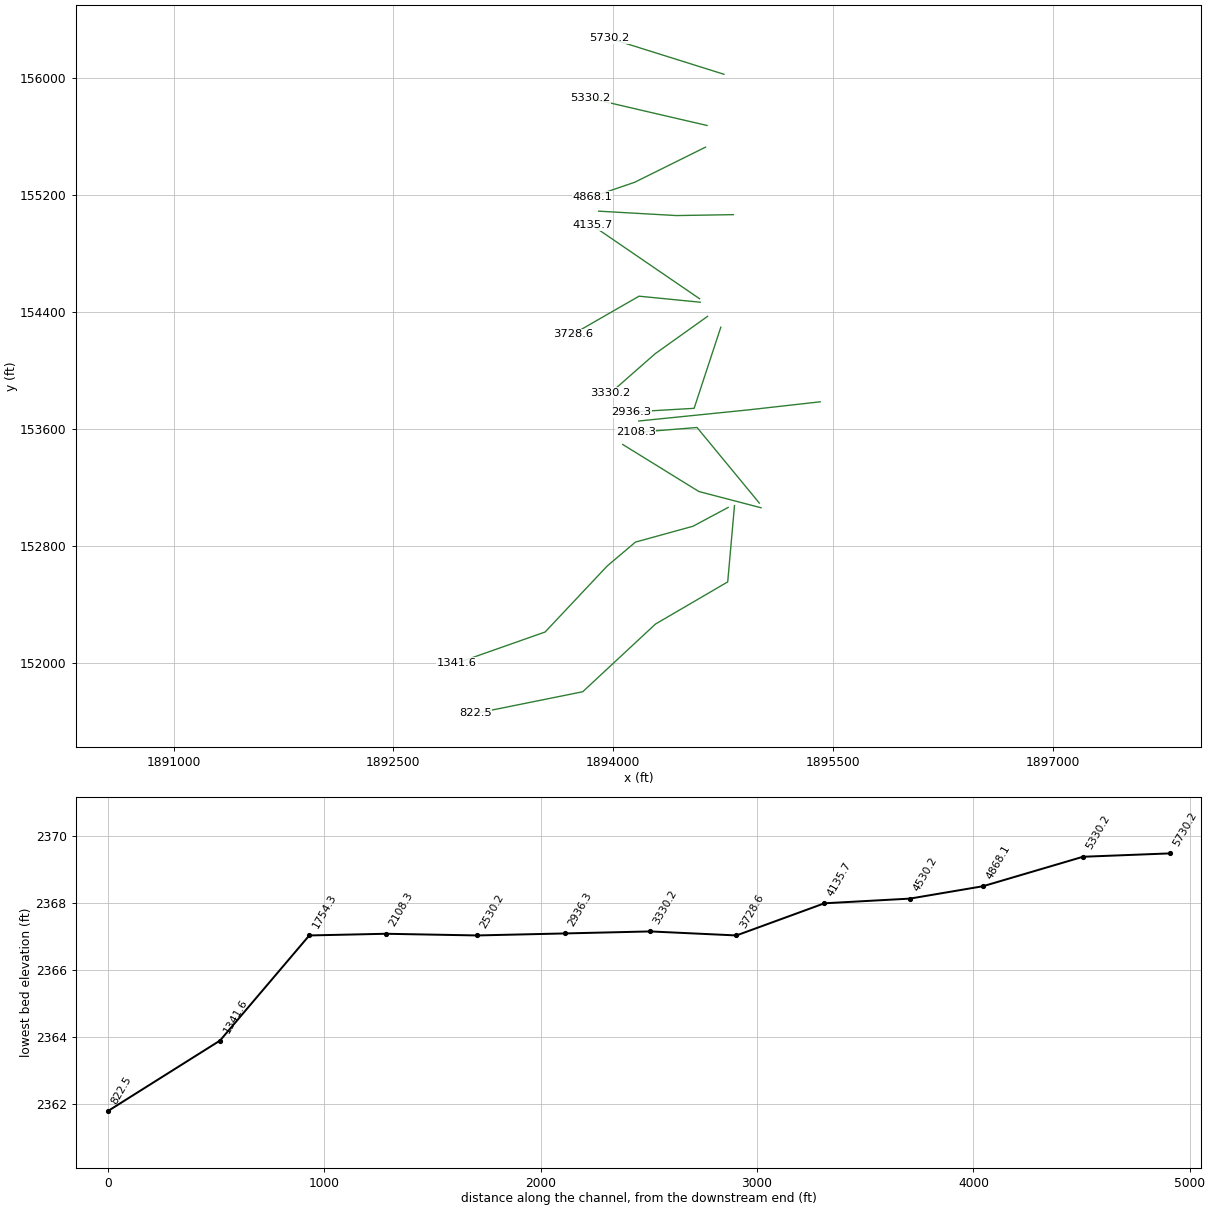
HEC-RAS study RghthndFrk.prj: RghthndFrk

--- RghthndFrk.g01 (geometry) --- (continued)

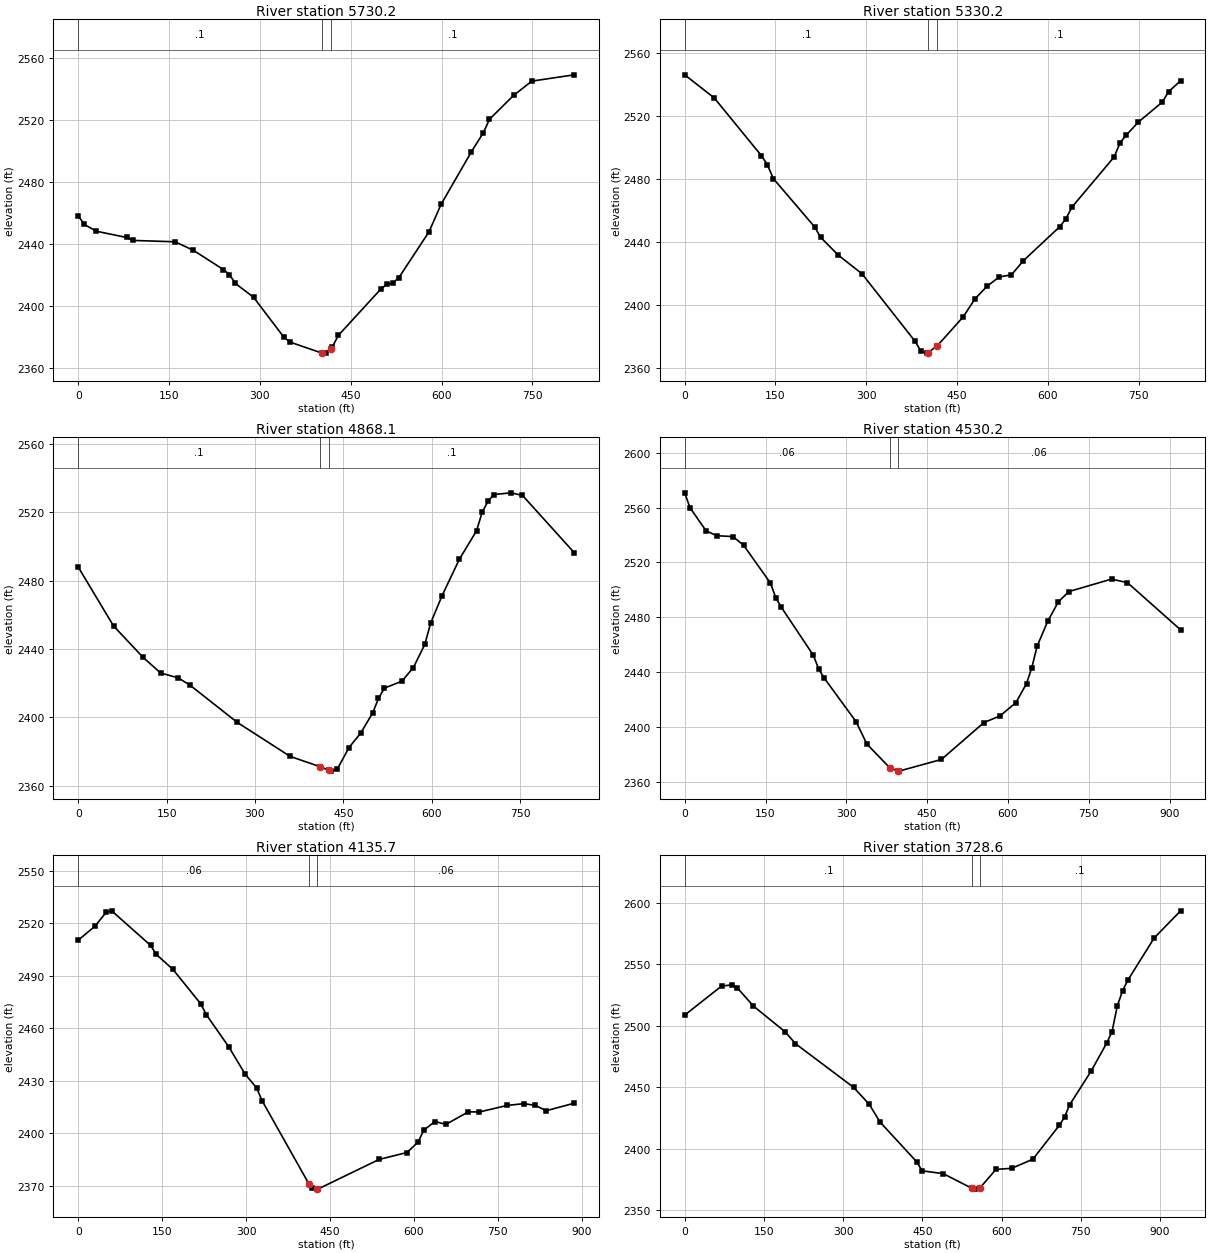
Type RM Length L Ch R = 1 ,5730.2  ,398.3,400,401.7
XS GIS Cut Line= 3
     1894755.738      156022.509     1894365.078      156145.288
     1893974.417      156268.067
#Sta/Elev= 30
       0 2458.07      10 2452.48      30 2448.08    79.9 2444.05    89.9 2442.17
   159.8 2441.27   189.8 2435.87   239.7 2423.38   249.7 2420.14   259.7 2414.39
   289.6 2405.49   339.6 2379.78   349.6 2376.62     402 2369.59   409.5 2369.49
     417 2372.38   419.5 2373.34   429.5 2380.88   499.4 2410.66   509.4 2413.85
   519.4 2414.62   529.4 2418.08   579.3 2447.72   599.3 2465.44   649.2 2499.24
   669.2  2511.7   679.2 2520.28   719.1 2535.69   749.1 2544.86     819 2548.92
#Mann= 3 , 0 , 0
       0      .1       0     402    .045       0     417      .1       0
Bank Sta=402,417
XS Rating Curve= 0 ,0
Exp/Cntr=0.3,0.1

Type RM Length L Ch R = 1 ,5330.2  ,446.4,462.1,477.7
XS GIS Cut Line= 3
      1894640.32      155672.522     1894240.948      155765.322
     1893842.388      155858.253
#Sta/Elev= 30
       0 2546.09    48.8 2531.45   126.9  2494.7   136.7 2488.96   146.4 2480.23
   214.8 2449.48   224.5 2442.94   253.8  2431.6   292.9 2419.78   380.7 2376.87
   390.5 2370.47   400.2 2369.39   402.5 2369.78   417.5 2374.12   459.9 2392.32
   479.9    2404   499.8 2411.94   519.8 2417.79   539.8 2419.09   559.7 2428.12
   619.6 2449.66   629.6 2454.54   639.6 2462.01   709.5 2493.96   719.4 2503.04
   729.4 2507.76   749.4 2516.05   789.3 2528.86   799.3 2535.38   819.3 2542.31
#Mann= 3 , 0 , 0
       0      .1       0   402.5    .045       0   417.5      .1       0
Bank Sta=402.5,417.5
XS Rating Curve= 0 ,0
Exp/Cntr=0.3,0.1

Type RM Length L Ch R = 1 ,4868.1  ,347.8,337.9,326.3
XS GIS Cut Line= 3
     1894630.259       155524.36     1894146.943      155284.321
     1893861.013      155186.528
#Sta/Elev= 30
       0 2487.94      60 2453.45   109.9 2435.16   139.9 2425.94   169.9 2423.06
   189.9 2418.78   269.8 2397.07   359.8 2377.11   410.6  2371.1   425.6 2368.96
   429.7 2368.51   439.7 2369.66   459.7 2382.32   479.7 2390.87   499.7 2402.52
   509.7 2411.04   519.7 2417.08   549.4 2421.14   568.9  2429.1   588.4 2442.73
   598.1 2455.01   617.6 2471.19   646.9 2492.44   676.1 2509.16   685.9 2520.26
   695.6 2526.39   705.4 2530.37   734.6 2531.37   754.1 2529.86   841.8 2496.41
#Mann= 3 , 0 , 0
       0      .1       0   410.6    .045       0   425.6      .1       0
Bank Sta=410.6,425.6
XS Rating Curve= 0 ,0
Exp/Cntr=0.3,0.1

Type RM Length L Ch R = 1 ,4530.2  ,408.9,394.9,382.5
XS GIS Cut Line= 3
     1894819.805       155062.98     1894432.087      155056.623
     1893900.302      155086.711
#Sta/Elev= 30
       0  2570.7     9.9 2559.85    39.8 2543.01    59.7 2539.48    89.5 2538.87
   109.4 2532.52   159.1 2505.09     169 2494.46     179 2487.63   238.6 2452.55
   248.6 2442.67   258.5  2436.1   318.2 2404.09   338.1 2387.88   380.3 2370.67
   395.3 2368.23   397.6 2368.14   476.5 2376.64   555.4  2403.5     585 2408.28
   614.6 2417.95   634.4 2431.85   644.2  2443.4   654.1 2459.07   673.8 2477.26
   693.5  2491.4   713.3 2498.88   792.2 2507.91   821.8  2505.3   920.4 2470.97
#Mann= 3 , 0 , 0
       0     .06       0   380.3    .045       0   395.3     .06       0
Bank Sta=380.3,395.3
XS Rating Curve= 0 ,0
Exp/Cntr=0.3,0.1

Type RM Length L Ch R = 1 ,4135.7  ,380.8,406.5,432.1
XS GIS Cut Line= 2
     1894589.482      154488.245     1893858.114      154989.276
#Sta/Elev= 30
       0 2510.45    29.9 2518.41    49.8 2526.33    59.8 2527.23   129.5 2507.43
   139.4 2502.33   169.3 2493.72   219.1 2473.99   229.1 2467.76     269 2449.46
   298.8 2433.61   318.8 2425.96   328.7 2418.57   412.6 2370.87   418.4 2368.43
   427.6 2368.03   428.3    2368   537.9    2385   587.7 2388.94   607.6 2394.96
   617.6  2401.7   637.5 2406.68   657.4 2405.06   697.3 2412.22   717.2 2412.15
     767 2415.91   796.9 2416.91   816.8 2415.91   836.7 2412.88   886.5 2417.15
#Mann= 3 , 0 , 0
       0     .06       0   412.6    .045       0   427.6     .06       0
Bank Sta=412.6,427.6
XS Rating Curve= 0 ,0
Exp/Cntr=0.3,0.1

Type RM Length L Ch R = 1 ,3728.6  ,396.1,398.4,402.9
XS GIS Cut Line= 3
     1894594.132      154464.328      1894176.61      154505.551
     1893726.452      154246.427
#Sta/Elev= 30
       0 2508.72    69.9  2532.4    89.9 2533.34    99.9 2530.81   129.9 2516.17
   189.8 2495.29   209.8 2485.48   319.7 2449.95   349.6 2436.04   369.6  2421.8
   439.5 2389.18   449.5 2381.94   489.5 2379.65   543.7 2367.75   549.4 2367.04
   558.7 2367.84   589.4  2383.1   619.3 2383.99   659.3 2391.42   709.2 2418.91
   719.2 2425.68   729.2 2435.94   769.2 2462.84   799.1 2486.03   809.1 2495.16
   819.1 2516.19   829.1 2528.52   839.1 2537.23     889 2571.56     939 2593.64
#Mann= 3 , 0 , 0
       0      .1       0   543.7    .045       0   558.7      .1       0
Bank Sta=543.7,558.7
XS Rating Curve= 0 ,0
Exp/Cntr=0.3,0.1

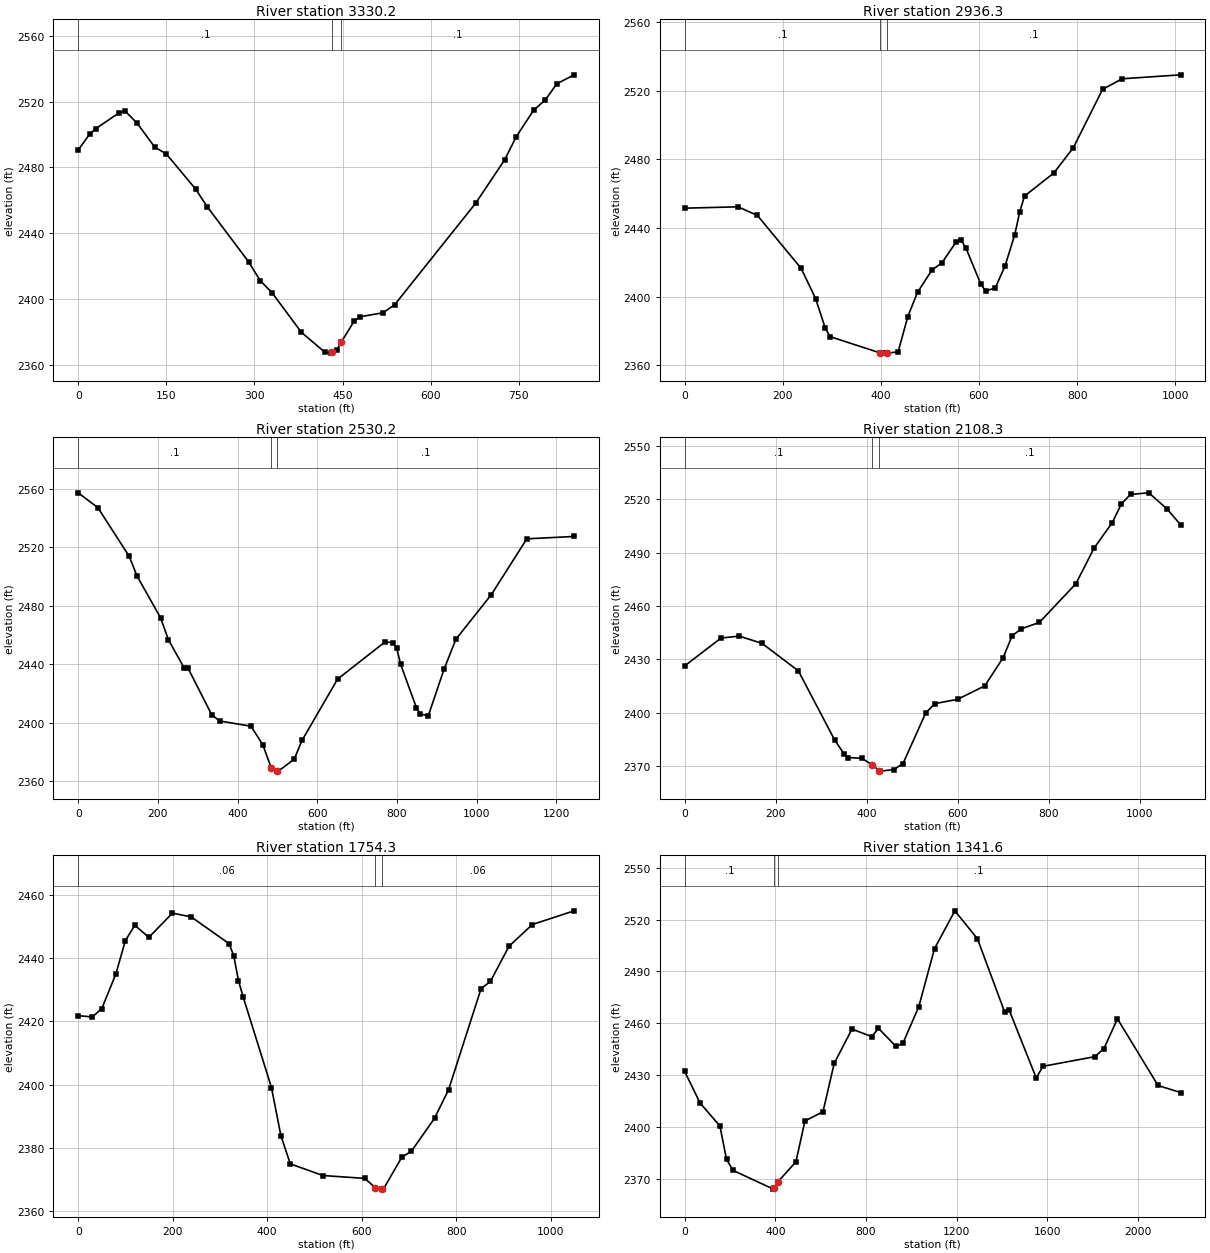
Type RM Length L Ch R = 1 ,3330.2  ,379.3,393.5,405.5
XS GIS Cut Line= 3
     1894644.055      154367.752     1894286.109      154112.081
     1893982.714      153845.049
#Sta/Elev= 30
       0  2490.6      20 2500.47      30 2503.55      70  2513.3      80 2514.15
     100 2507.01     130 2492.42     150 2488.15   199.9  2466.8   219.9 2455.93
   289.9  2422.7   309.9 2411.11   329.9 2403.84   379.9 2379.77   419.9 2367.67
   429.9 2367.16   432.4 2367.62   439.9 2369.02   447.4 2373.68   469.4 2386.48
   479.3 2389.24   518.7 2391.68   538.5 2396.56   676.5 2458.31   725.8 2484.68
   745.5 2498.68     775 2514.77   794.8 2520.95   814.5 2530.82     844 2536.26
#Mann= 3 , 0 , 0
       0      .1       0   432.4    .045       0   447.4      .1       0
Bank Sta=432.4,447.4
XS Rating Curve= 0 ,0
Exp/Cntr=0.3,0.1

Type RM Length L Ch R = 1 ,2936.3  ,432,406.1,380
XS GIS Cut Line= 3
     1894734.377      154293.521     1894552.398      153739.141
     1894125.643      153714.232
#Sta/Elev= 30
       0 2451.62   108.8 2452.41   148.3 2447.37   237.4 2416.53     267 2398.85
   286.8 2381.47   296.7 2376.69   398.1 2367.26   405.5  2367.1   413.1  2367.1
   435.1 2367.86   454.9 2388.43   474.7 2402.58   504.4 2415.68   524.2 2419.66
   553.8  2432.1   563.7 2432.91   573.6 2428.22   603.4  2407.5   613.3 2403.32
   633.2 2405.09   653.1 2417.95     673 2436.26   682.9 2449.35   692.8 2458.68
   752.5 2472.15   792.2 2486.82   851.9 2520.89   891.7 2527.06    1011 2529.37
#Mann= 3 , 0 , 0
       0      .1       0   398.1    .045       0   413.1      .1       0
Bank Sta=398.1,413.1
XS Rating Curve= 0 ,0
Exp/Cntr=0.3,0.1

Type RM Length L Ch R = 1 ,2530.2  ,443.9,421.8,399.8
XS GIS Cut Line= 3
     1895412.754      153783.643     1894923.139      153728.461
     1894174.667      153652.445
#Sta/Elev= 30
       0 2557.21    49.3  2547.1   128.1 2513.76   147.8 2500.29   206.9 2471.74
   226.6 2456.72   266.1 2437.51   275.9 2437.29     335 2405.62   354.8 2401.33
   433.6 2397.74   463.2 2385.15   485.2 2368.87   500.2 2367.11   502.6 2367.04
   542.2 2375.22     562 2388.11   651.1 2429.91   769.9 2455.24   789.7 2454.87
   799.6 2451.07   809.5 2439.93   849.1 2410.35     859 2406.13   878.8 2404.81
   918.4 2436.68   948.1 2457.14  1037.2 2487.71  1126.2 2525.78    1245  2527.4
#Mann= 3 , 0 , 0
       0      .1       0   485.2    .045       0   500.2      .1       0
Bank Sta=485.2,500.2
XS Rating Curve= 0 ,0
Exp/Cntr=0.3,0.1

Type RM Length L Ch R = 1 ,2108.3  ,346.3,353.7,361.1
XS GIS Cut Line= 3
      1894997.41      153091.402     1894572.176       153608.11
     1894153.592      153574.095
#Sta/Elev= 30
       0 2426.31    79.9 2442.01   119.8 2443.08   169.8 2439.02   249.7 2423.52
   329.6  2384.5   349.6 2376.96   359.6 2374.75   389.5 2374.28   412.2 2370.54
   427.2  2367.4   429.5 2367.09   459.4 2367.96   479.4 2371.32   529.4 2399.83
   549.3 2405.08   599.3  2407.5   659.2  2415.1   699.2 2430.88   719.2 2443.28
   739.2 2447.16   779.2 2450.83   859.2 2472.59   899.2 2492.65   939.2    2507
   959.2 2517.57   979.2 2522.84  1019.2 2523.74  1059.2 2514.74  1089.2 2505.73
#Mann= 3 , 0 , 0
       0      .1       0   412.2    .045       0   427.2      .1       0
Bank Sta=412.2,427.2
XS Rating Curve= 0 ,0
Exp/Cntr=0.3,0.1

Type RM Length L Ch R = 1 ,1754.3  ,394.2,412.6,431.1
XS GIS Cut Line= 3
     1895009.194      153059.313     1894584.538      153170.515
     1894065.357      153491.913
#Sta/Elev= 30
       0 2421.81    29.9 2421.41    49.9 2424.04    79.8 2435.04    99.8 2445.52
   119.7 2450.33   149.6 2446.56   199.5  2454.2   239.4 2452.98   319.2 2444.56
   329.2 2440.73   339.2 2432.85   349.2 2427.68     409 2399.11     429 2383.89
   448.8 2375.03   517.8 2371.34   606.4 2370.43   628.3 2367.55   643.3 2367.05
   645.8 2367.04   685.2  2377.2   704.9 2378.95   754.1 2389.42   783.7 2398.37
   852.6 2430.34   872.3 2432.62   911.7 2443.72     961 2450.59  1049.6 2454.92
#Mann= 3 , 0 , 0
       0     .06       0   628.3    .045       0   643.3     .06       0
Bank Sta=628.3,643.3
XS Rating Curve= 0 ,0
Exp/Cntr=0.3,0.1

Type RM Length L Ch R = 1 ,1341.6  ,491.2,519,544.5
XS GIS Cut Line= 6
     1894784.793      153061.735     1894544.981      152933.176
     1894151.904      152824.612      1893958.78      152660.934
     1893535.516       152210.15     1892934.475      151998.262
#Sta/Elev= 30
       0 2432.05      68 2413.73   155.5 2400.46   184.6 2381.14   213.8 2374.72
   391.4  2363.9   395.6 2364.66   410.6 2368.05   490.9 2379.69   530.7 2403.38
   610.3 2408.69     660 2436.76   738.3 2456.56   825.9 2452.21   855.2    2457
     933 2446.49     963 2448.36  1032.8 2469.38  1102.6 2503.15  1192.4 2525.04
  1292.1 2508.84  1411.8 2466.57  1431.7 2467.71  1551.4 2428.26  1581.3 2435.02
  1810.3  2440.6  1850.1 2445.25  1909.9  2462.5  2089.1 2423.91  2188.7 2419.83
#Mann= 3 , 0 , 0
       0      .1       0   395.6    .045       0   410.6      .1       0
Bank Sta=395.6,410.6
XS Rating Curve= 0 ,0
Exp/Cntr=0.3,0.1

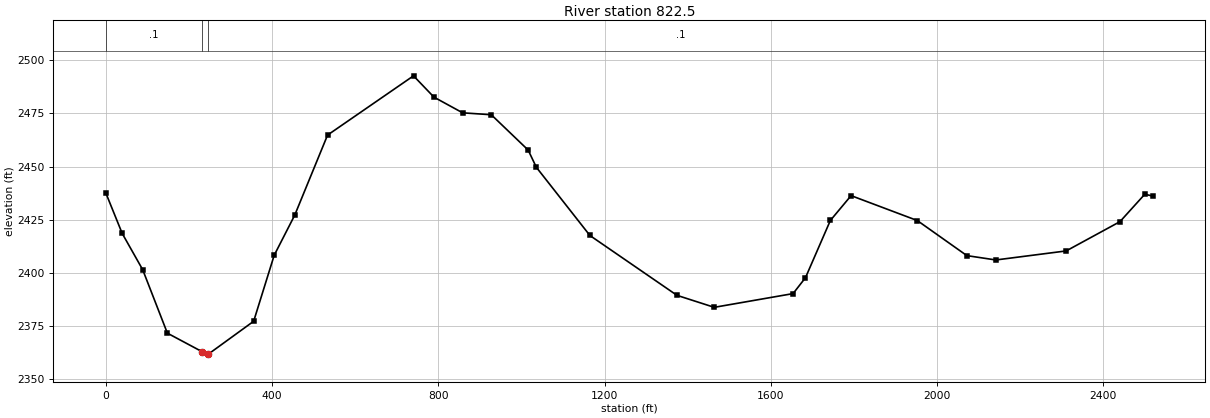
Type RM Length L Ch R = 1 ,822.5   ,861.2,822.5,783.3
XS GIS Cut Line= 5
     1894827.876      153074.331      1894781.54      152552.647
     1894288.384      152264.403     1893792.231      151801.874
     1893060.596      151653.988
#Sta/Elev= 30
       0 2437.64    39.5 2418.56    88.9 2401.47   148.2 2371.65   231.8 2362.93
   246.8 2361.79   355.8 2377.25   405.2 2408.29   454.6 2427.15   533.6 2464.82
   740.4 2492.69   789.6 2482.66   858.6 2475.29   927.5 2474.39  1016.2 2457.78
  1035.9 2449.68  1164.8 2417.59  1374.3 2389.44    1464  2383.8  1653.6 2390.26
  1683.5 2397.76  1743.3 2424.66  1793.2 2436.34  1952.4 2424.63  2071.8 2408.12
  2141.5 2406.08  2310.7 2410.33  2440.1  2424.1  2499.8 2436.99  2519.7 2436.12
#Mann= 3 , 0 , 0
       0      .1       0   231.8    .045       0   246.8      .1       0
Bank Sta=231.8,246.8
XS Rating Curve= 0 ,0
Exp/Cntr=0.3,0.1

Chan Stop Cuts=-1
Use User Specified Reach Order=0
Composite Channel Slope=5